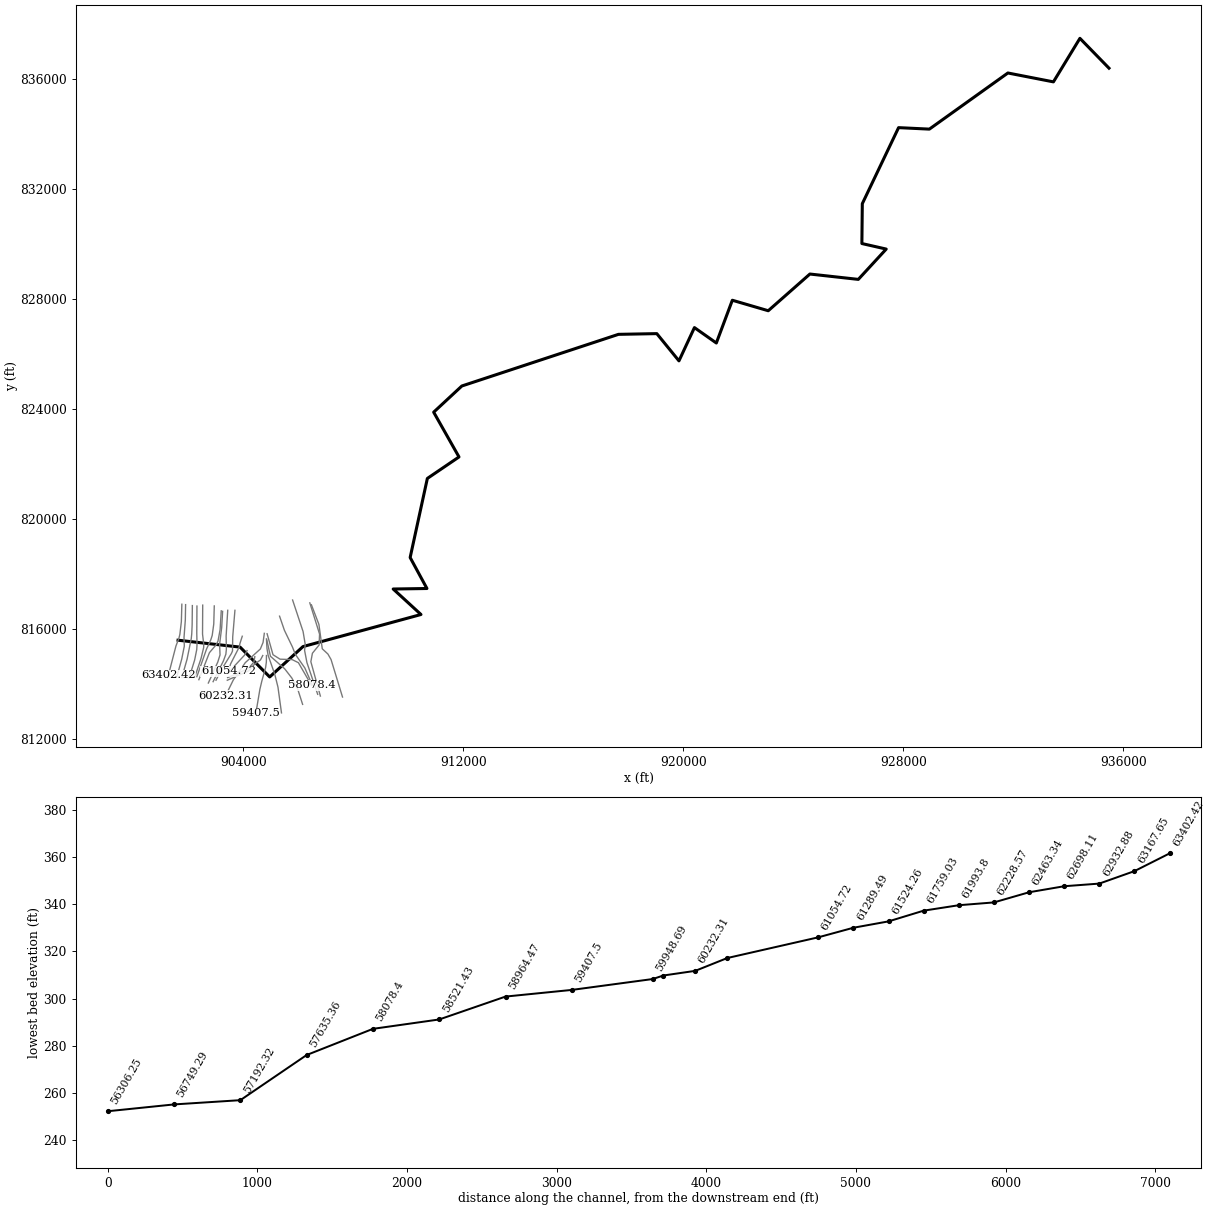
--- 16296_ras.prj (project) ---

Proj Title=16296
Current Plan=p01
Default Exp/Contr=0.3,0.1
English Units
Geom File=g01
Flow File=f01
Plan File=p01
Y Axis Title=Elevation
X Axis Title(PF)=Main Channel Distance
X Axis Title(XS)=Station
BEGIN DESCRIPTION:
RFD model 16296 exported to HEC-RAS
END DESCRIPTION:

--- 16296_ras.p01 (plan) ---

Plan Title=Plan 01
Program Version=4.10
Short Identifier=Plan 01
Geom File=g01
Flow File=f01
Subcritical Flow
Calc Critical at every XS
Secant Critical Depth

--- 16296_ras.f01 (steady flow) ---

Flow Title=Flow 01
Program Version=5.01
Number of Profiles= 6
Profile Names=10yr,25yr,50yr,100yr,100plus,500yr
River Rch & RM=16296,65,63402.42
 6950.74 9115.4910841.6711868.0317327.3214379.82
River Rch & RM=16296,65,63167.65
 6962.39 9133.2910864.8211895.3317367.1814413.51
River Rch & RM=16296,65,62932.88
 6979.36 9159.6710899.4211936.4117427.1514464.87
River Rch & RM=16296,65,62698.11
 6989.58 9175.5610920.2811961.1717463.3114495.83
River Rch & RM=16296,65,62463.34
 7020.91  9224.210984.0512036.8617573.8114590.31
River Rch & RM=16296,65,62228.57
 7024.13  9229.2 10990.612044.6317585.1514600.01
River Rch & RM=16296,65, 61993.8
 7060.37 9285.7811065.0112133.1417714.3914710.93
River Rch & RM=16296,65,61759.03
 7071.09 9302.4611086.9112159.1617752.3814743.44
River Rch & RM=16296,65,61524.26
 7076.63 9311.2211098.5112173.0417772.64   14761
River Rch & RM=16296,65,61289.49
  7084.9 9324.3311115.8812193.8217802.9714787.33
River Rch & RM=16296,65,61054.72
  7092.6 9336.5411132.07 12213.217831.2714811.88
River Rch & RM=16296,65, 60446.2
 7106.35 9358.3411160.9612247.7817881.7714855.69
River Rch & RM=16296,65,60232.31
 7161.09 9443.35 11272.512380.2718075.1915020.83
River Rch & RM=16296,65,60018.42
 7165.21 9449.8811281.1512390.61 18090.315033.91
River Rch & RM=16296,65,59948.69
 7166.04 9451.1811282.8812392.6818093.3215036.52
River Rch & RM=16296,65, 59407.5
 7182.62 9477.5311317.85 12434.618154.5115089.65
River Rch & RM=16296,65,58964.47
  7203.5 9511.0511362.5612488.3918233.0515158.34
River Rch & RM=16296,65,58521.43
 7212.41  9525.411381.7412511.4818266.7715187.86
River Rch & RM=16296,65, 58078.4
  7220.5 9538.4411399.1712532.4918297.4415214.76
River Rch & RM=16296,65,57635.36
 7233.54 9559.4611427.2712566.3618346.8915258.12
River Rch & RM=16296,65,57192.32
 9239.7612523.8315223.7616994.04 24811.320441.73
River Rch & RM=16296,65,56749.29
 9299.0612616.3815346.0317140.3625024.92 20619.1
River Rch & RM=16296,65,56306.25
 9307.4412629.6715363.7217161.6725056.0420645.26
River Rch & RM=16296,65,55875.25
 9320.2312649.9615390.7617194.24 25103.620685.26
River Rch & RM=16296,65,55043.98
 9370.2112729.3115496.5417321.7425289.7420841.88
River Rch & RM=16296,65,54480.81
 9379.3212743.8815516.0417345.3125324.1520871.01
River Rch & RM=16296,65,53973.15
 9387.6612757.2515533.9417366.9825355.7920897.82
River Rch & RM=16296,65,53404.83
 9395.2612769.4515550.2917386.7725384.6820922.32
River Rch & RM=16296,65,52050.04
10997.3315267.53 18854.621348.6331169.0125664.99
River Rch & RM=16296,65,50568.98
11022.8215307.7818908.2621413.43 31263.625742.65
River Rch & RM=16296,65,49073.31
11035.6815328.1418935.45 21446.3 31311.625782.16
River Rch & RM=16296,65,48022.51
11089.9715413.6319049.2821583.6131512.0825946.25
River Rch & RM=16296,65,47598.82
12464.5717429.6821628.7324593.3935906.3429251.85
River Rch & RM=16296,65,47322.82
12584.0917616.0121875.7124890.2936339.8329597.32
River Rch & RM=16296,65,46911.75
12596.0517634.9321900.9924920.8836384.4929633.38
River Rch & RM=16296,65,46500.67
12709.7117812.2922136.2425203.8636797.6429962.49
River Rch & RM=16296,65,46089.59
12740.4117860.9622201.3425282.7236912.78 30055.5
River Rch & RM=16296,65,45678.51
12753.2717881.3822228.6925315.8836961.1930094.66
River Rch & RM=16296,65,44495.65
12802.3417959.5122333.4625443.0437146.8430245.15
River Rch & RM=16296,65,42446.34
 13766.219456.2824314.5427822.5640620.9532980.48
River Rch & RM=16296,65,41669.78
14373.8720344.3525449.2229145.0842551.8234384.27
River Rch & RM=16296,65,40742.24
15249.5621613.57 27062.731017.0845284.9336333.39
River Rch & RM=16296,65,39348.13
15350.1921769.7927269.5931265.7545647.9936613.38
River Rch & RM=16296,65,38739.17
15357.2821781.4527285.53 31285.445676.6836636.72
River Rch & RM=16296,65,38522.81
15361.7821788.8327295.6131297.8245694.8236651.46
River Rch & RM=16296,65,37001.27
15410.5321869.7627406.7131435.2845895.5136815.92
River Rch & RM=16296,65,35517.83
 15828.622533.1228296.1732515.4547472.5638055.44
River Rch & RM=16296,65,33926.08
16139.9623059.5229026.1433426.0848802.0739156.09
River Rch & RM=16296,65,32194.78
16148.4923075.3129048.9833455.48   4884539193.79
River Rch & RM=16296,65,30177.27
16583.5223792.4330031.2534669.5250617.4940627.65
River Rch & RM=16296,65,28609.02
 16631.123879.7230157.1934831.4750853.9540833.88
River Rch & RM=16296,65,25826.54
 17772.225767.5132750.5238045.9155547.0344619.57
River Rch & RM=16296,65,23316.48
17806.6225835.1132851.1938178.4855740.5844793.97
River Rch & RM=16296,65,21880.98
17827.3725877.82   3291638264.9555866.8244910.28
River Rch & RM=16296,65,19628.05
17850.7525927.0132991.2838365.9456014.2745047.43
River Rch & RM=16296,65,16625.66
17870.0425968.2833054.8638451.6156139.3645164.61
River Rch & RM=16296,65,14433.84
18380.6326959.4434526.15 40386.458964.15 47696.2
River Rch & RM=16296,65,14146.42
18385.1826969.0534540.9340406.3258993.2247723.34
River Rch & RM=16296,65,12738.74
18426.6827056.4634675.1640587.1459257.2347969.48
River Rch & RM=16296,65,12386.38
18429.4727062.34 34684.240599.32   5927547986.06
River Rch & RM=16296,65, 11103.3
18740.1627691.12 35635.841869.25 61129.149684.88
River Rch & RM=16296,65, 8678.08
18895.38 28011.636125.2942527.0762089.5250573.93
River Rch & RM=16296,65,6223.717
19068.6728365.1536663.2243248.4163142.6851543.95
River Rch & RM=16296,65, 4787.06
19086.74 28402.536720.3643325.3763255.0451648.12
River Rch & RM=16296,65,       0
19831.6629829.5338838.0246118.3967332.8455279.32
Boundary for River Rch & Prof#=16296,65,1
Up Type= 0
Dn Type= 2
Boundary for River Rch & Prof#=16296,65,2
Up Type= 0
Dn Type= 2
Boundary for River Rch & Prof#=16296,65,2
Up Type= 0
Dn Type= 2
Boundary for River Rch & Prof#=16296,65,2
Up Type= 0
Dn Type= 2
Boundary for River Rch & Prof#=16296,65,2
Up Type= 0
Dn Type= 2
Boundary for River Rch & Prof#=16296,65,2
Up Type= 0
Dn Type= 2

--- 16296_ras.g01 (geometry) ---

Geom Title=16296
Program Version=4.10

River Reach=16296,65
Reach XY= 30
901623.923323396815600.119397111903880.492764622815349.064727638
904957.714272324814263.185100846906167.080321193815367.216299716
910460.602567049816534.987715079909449.400311741817462.340100926
910677.307576479 817480.53492318 910066.07131705818607.904381726
 910692.14848328821484.207335776911843.082312375822265.507101495
 910921.54006702823894.362715014911947.094216885824846.579926059
917642.894233644826725.091881674919037.425483706 826751.13354835
919843.632080943825760.356638619920406.388734729826970.377679313
921202.790067049826409.987715024921784.922590196827965.507101586
923090.982657345827583.605372509924606.103145749828918.632101571
926366.947486312828724.006749338927382.144812407829826.618212661
926496.728145718830028.007101575926512.353145719831477.659879325
927831.797590167834243.284879307928951.589256856 834189.46543486
931807.492034615836231.132101525933463.742034616835908.215434838
934427.283701271837491.548768187 935484.57536796836406.479323745

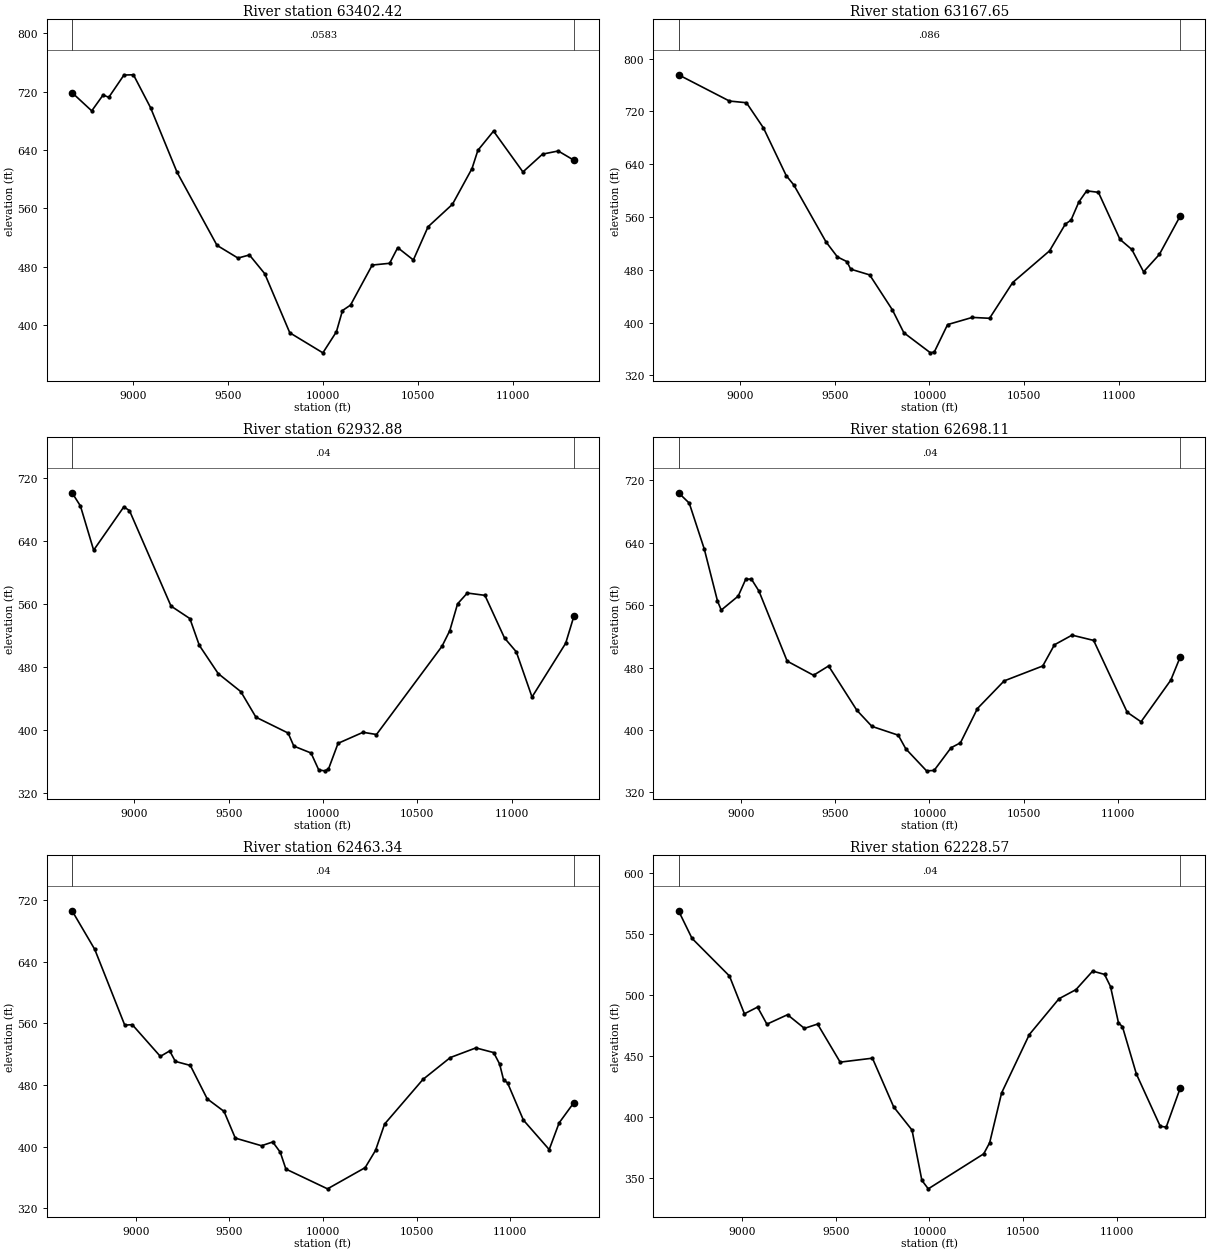
Type RM Length L Ch R = 1 ,63402.42,234.769300,234.769300,234.769300
XS GIS Cut Line= 6
901762.424901446 816908.74007619901744.740988619816278.139375444
901690.833542174815815.158583653901656.252228621 815673.07608947
901548.158275928815390.347972794901271.999636386814325.244225995
#Sta/Elev= 30
8676.415718.62298780.156693.62438840.161715.43948870.165712.22818950.175742.8151
9000.182743.15579090.248698.15099230.416609.26289441.005509.04099551.585491.6036
9612.055495.84739692.838470.13949825.003389.03879999.587361.514210071.03390.4771
10103.02419.594910145.33427.024110259.88482.006510351.59484.408710394.33505.9042
10476.87 488.98410554.58534.5863 10683.2565.425910786.37614.496110817.32639.4833
10899.86665.853811054.95609.791911158.39634.244211241.13638.560211323.63625.9175
#Mann= 3 , 0 , 0
8676.415  0.0583       08676.415  0.0583       011323.63  0.0583       0
#XS Ineff= 2 , 0
       0                               0
Bank Sta=8676.415,11323.63
Exp/Cntr=0.3,0.1

Type RM Length L Ch R = 1 ,63167.65,234.769400,234.769400,234.769400
XS GIS Cut Line= 6
901898.662639677816893.925920618901889.008295622816337.282191139
901841.383933954815697.916349476901852.559140907815386.518334522
901758.575144162814916.058383422901583.222712884814278.285381097
#Sta/Elev= 30
8673.832775.66748942.768735.85489032.797733.26839122.847694.98579242.931622.8365
9283.005608.65629453.322 522.2559513.523499.50049563.719492.34239583.797480.9223
9684.187472.18169804.632418.95569864.731 384.49410005.47354.017310025.75355.3408
10095.92396.842110226.58407.7411 10317.8406.409610440.07460.642210634.93508.6916
10718.17549.174410748.46555.325810789.82582.809210831.17 599.689 10893.2597.3897
 11007.2526.053211069.59510.822611131.99476.840511215.17503.197611326.14561.7679
#Mann= 3 , 0 , 0
8673.832   0.086       08673.832   0.086       011326.14   0.086       0
#XS Ineff= 2 , 0
       0                               0
Bank Sta=8673.832,11326.14
Exp/Cntr=0.3,0.1

Type RM Length L Ch R = 1 ,62932.88,234.769400,234.769400,234.769400
XS GIS Cut Line= 6
902144.743247984816859.395061876902136.726498522816158.448684142
 902121.99403634815829.949052676902104.544046162815658.920148448
901952.004068347 814908.99445067 901762.43674158814242.733203955
#Sta/Elev= 30
8669.976701.71328714.373684.92878784.376628.86298944.379683.83398974.379679.0467
9194.429557.91039294.456542.03699344.469508.05759444.529472.21029564.616449.2708
9644.735416.81999815.305396.70969845.538380.13459936.742371.37199977.637349.9034
10008.36348.737510028.83350.731410079.99383.661310212.53397.660510283.74394.8662
10631.07506.894610672.31526.688710713.59560.755210765.19574.447910858.52571.5132
 10962.4517.374311024.89499.802711108.23442.4608 11286.7510.699211330.03544.8921
#Mann= 3 , 0 , 0
8669.976    0.04       08669.976    0.04       011330.03    0.04       0
#XS Ineff= 2 , 0
       0                               0
Bank Sta=8669.976,11330.03
Exp/Cntr=0.3,0.1

Type RM Length L Ch R = 1 ,62698.11,234.769400,234.769400,234.769400
XS GIS Cut Line= 6
902311.683702975816841.835916481902305.075290165815865.760094796
902313.804060088 815436.84870567902304.130984543815261.136846802
 902227.17362382814877.050652452902022.264991786814216.788530357
#Sta/Elev= 30
8667.643703.8615 8724.48690.62628804.481631.67758874.482565.24798894.482553.5663
8984.485571.48029024.488593.1257 9054.49593.29829094.493578.00819244.503488.1653
9384.513470.06049464.519481.98119614.529425.23839694.534404.57929834.557393.2806
9874.575375.78969984.624347.618410024.64348.065710114.66377.1857 10164.7383.5222
10255.02427.483910396.75462.854810601.76481.962610663.79509.099710757.23521.4717
10872.02514.710111050.15 422.69911123.68410.470911281.58463.764411332.32493.8298
#Mann= 3 , 0 , 0
8667.643    0.04       08667.643    0.04       011332.32    0.04       0
#XS Ineff= 2 , 0
       0                               0
Bank Sta=8667.643,11332.32
Exp/Cntr=0.3,0.1

Type RM Length L Ch R = 1 ,62463.34,234.769400,234.769400,234.769400
XS GIS Cut Line= 6
902521.070028486816876.233376604902514.760718505815824.197969743
902558.288295319815452.069739433902556.216978429815334.300305334
902461.646276735814939.949797337902228.870737864 814250.70394844
#Sta/Elev= 30
8660.593705.97988781.831655.80938941.836557.51168981.838558.20099131.845 516.963
9181.854524.09149211.859510.48269291.872505.23859381.887461.92829471.902445.5849
9531.913410.93789671.916401.01539731.935405.89669771.976392.58699802.009370.7466
10024.32345.067210225.29372.601910280.55394.963910329.09 429.18910533.64487.0528
10679.91515.497810816.39528.002810911.24521.926510942.93507.127810964.12486.4682
 10985.3482.663811070.03434.297211207.71396.055611260.67430.689311339.35456.9174
#Mann= 3 , 0 , 0
8660.593    0.04       08660.593    0.04       011339.35    0.04       0
#XS Ineff= 2 , 0
       0                10155.98       0
Bank Sta=8660.593,11339.35
Exp/Cntr=0.3,0.1

Type RM Length L Ch R = 1 ,62228.57,234.769400,234.769400,234.769400
XS GIS Cut Line= 6
902941.895311735816846.910369917902923.181293873816187.436407515
902866.871906133815774.317319047902815.232992525815613.236409939
902662.436729809 815283.39688001902308.306095281814274.102769702
#Sta/Elev= 30
8659.934569.05178731.844546.42718931.864515.50159011.881 484.4889081.936489.9813
9131.975475.94579242.135483.72489332.329472.51389402.586476.0478 9523.26444.7805
9695.627448.03749809.093408.01879907.036389.03539959.686 347.7349993.816340.7672
10290.02 369.50910321.88378.677610385.58419.523110533.66467.454510692.17  496.85
10782.69504.307310871.82519.514110935.33 516.82910967.21506.852111009.72477.0983
11030.98473.908911105.37435.065311232.91392.123911264.79391.447811340.14423.6981
#Mann= 3 , 0 , 0
8659.934    0.04       08659.934    0.04       011340.14    0.04       0
#XS Ineff= 2 , 0
       0                10187.69       0
Bank Sta=8659.934,11340.14
Exp/Cntr=0.3,0.1

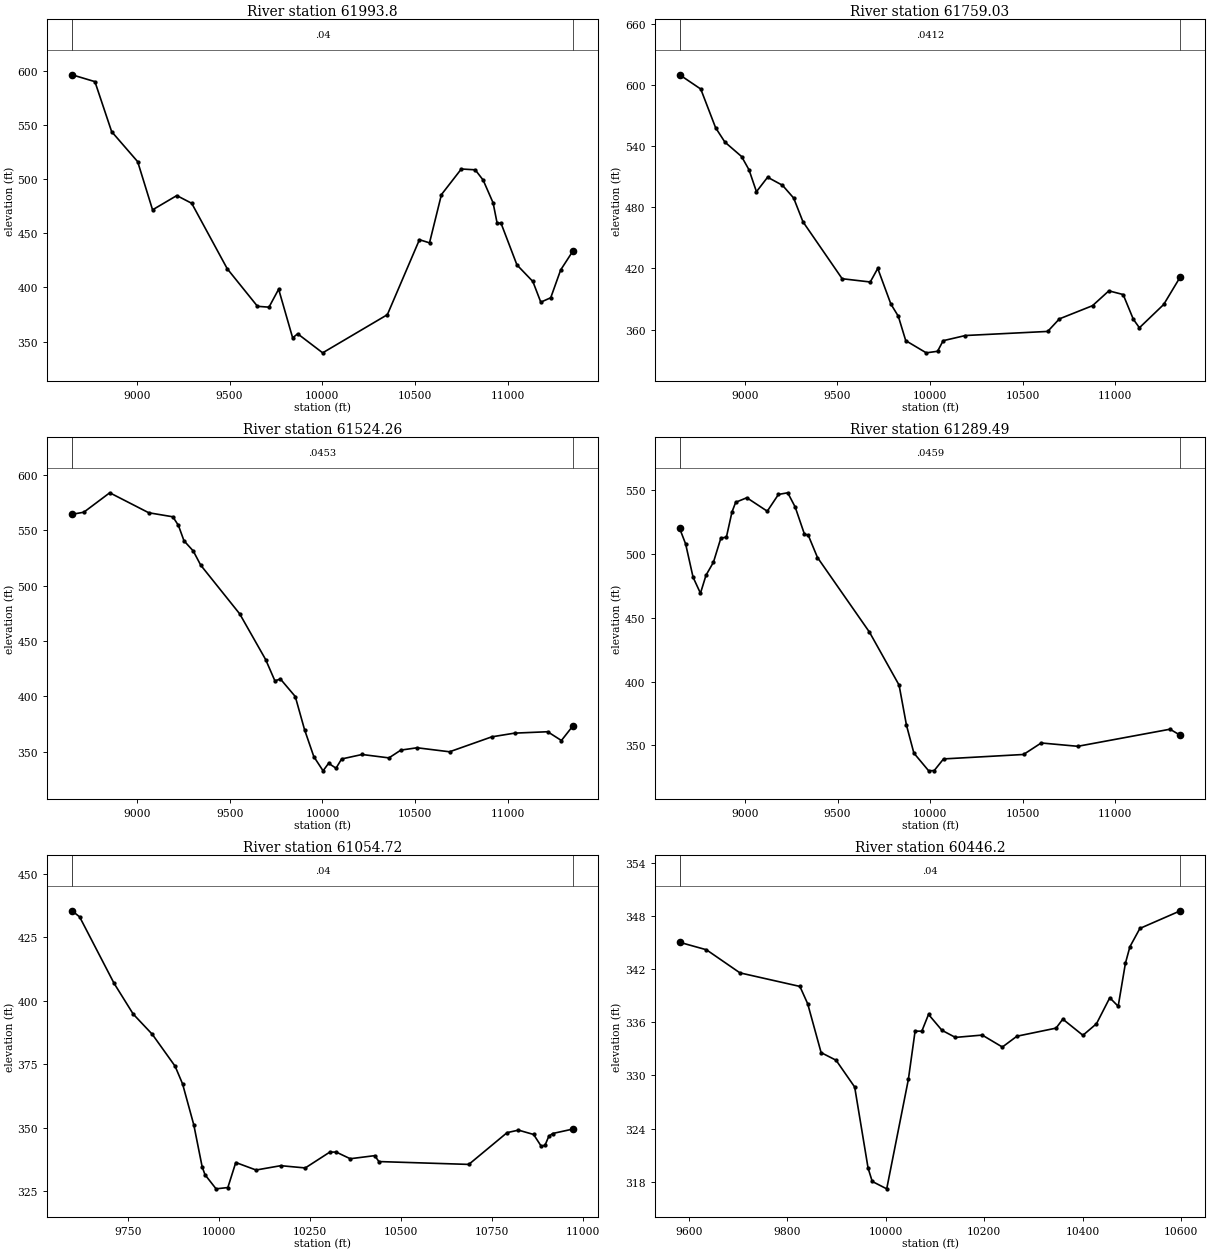
Type RM Length L Ch R = 1 , 61993.8,234.769300,234.769300,234.769300
XS GIS Cut Line= 6
903195.387702573816668.275932919903153.492166757 815982.34852319
903078.544061378815575.373554263903015.656380291815439.852681871
902765.922578282815147.299627376902381.012838709814164.120517162
#Sta/Elev= 30
8651.698596.53698775.023590.19788865.084544.00219005.271516.24799085.466471.7233
9215.912484.91739296.278477.77489487.728417.25649650.511382.58169712.368381.7787
9764.481398.39059839.842353.43639866.973357.179610001.54339.580910349.96374.8461
10522.62444.130410576.93441.218610641.14485.817610748.15509.470810823.06508.7169
10865.87499.202610919.37478.160910940.77 459.63810962.18459.308311047.79420.8221
 11133.4405.5216 11176.2386.416111229.71390.489611283.21416.178411348.36433.4485
#Mann= 3 , 0 , 0
8651.698    0.04       08651.698    0.04       011348.36    0.04       0
#XS Ineff= 2 , 0
       0                 10108.3       0
Bank Sta=8651.698,11348.36
Exp/Cntr=0.3,0.1

Type RM Length L Ch R = 1 ,61759.03,234.769400,234.769400,234.769400
XS GIS Cut Line= 6
903245.024706062816648.960723156903211.836789514816064.965768083
903136.230918754815458.881658094 903150.88907465815064.013979136
903070.567659518814809.266465969902726.098422544814042.656592789
#Sta/Elev= 30
  8649.2609.99268763.207595.99168843.295558.0329 8893.35543.9699 8983.49529.8048
9023.579516.75729063.669495.31169123.829509.51339204.107501.61589264.357489.1031
9314.598465.82069526.103  409.979677.638406.76699718.048420.0766  9788.7 385.204
9828.924373.19999869.028349.23829979.769337.279810040.75338.804710070.91349.1938
10191.18354.2723 10634.9358.279610697.97370.582310876.83383.533610964.91398.0815
11041.97394.458711096.97370.200211129.75361.866311260.81384.714111350.76411.9086
#Mann= 3 , 0 , 0
  8649.2  0.0412       0  8649.2  0.0412       011350.76  0.0412       0
#XS Ineff= 2 , 0
       0                10087.29       0
Bank Sta=8649.2,11350.76
Exp/Cntr=0.3,0.1

Type RM Length L Ch R = 1 ,61524.26,234.769400,234.769400,234.769400
XS GIS Cut Line= 6
903431.228852462816688.610357594903373.161466163815747.555300167
903381.462040181815265.852823123903363.389968245815091.038598604
903275.007718109814848.975325179902899.179429592814092.183098602
#Sta/Elev= 30
8647.872564.61178711.506566.4976 8851.64  584.079062.016566.02299192.377  562.36
 9222.47554.58919252.563540.66629302.718531.44179342.842518.66059553.328474.6496
9693.432433.35159743.433414.12389773.445415.72759853.514399.91799903.558370.0039
9953.602345.621810003.64332.739510033.64339.595210073.64335.081810103.66343.4562
10214.28347.511610359.39344.443910423.85351.481710511.47353.590410686.74349.9616
10914.83363.467611038.18366.826911216.52368.082311290.81360.1508 11352.1 373.213
#Mann= 3 , 0 , 0
8647.872  0.0453       08647.872  0.0453       0 11352.1  0.0453       0
#XS Ineff= 2 , 0
       0                10143.01       0
Bank Sta=8647.872,11352.1
Exp/Cntr=0.3,0.1

Type RM Length L Ch R = 1 ,61289.49,234.769400,234.769400,234.769400
XS GIS Cut Line= 6
 903693.34065624816687.480085441903612.555691858815721.390966613
903605.043496461815210.599135341903566.798500497815120.548149416
903215.015331691814549.899772766903004.659349269814144.788402959
#Sta/Elev= 30
8646.595520.14318679.102  507.928719.136481.91378759.169469.27818789.195483.4166
8829.259493.59048869.369512.46898899.451 513.3058929.533 532.9898949.588540.6127
9009.752544.17699120.344533.61699180.669546.75749230.939548.06599271.156536.9053
9321.426515.52479341.534514.88869391.805497.27989672.759438.78189832.807397.2648
 9872.83365.75199912.873343.9364 9992.95330.043610022.95330.298510073.03339.3864
 10505.4342.870510601.09351.895210798.73349.283211297.25362.682411353.31357.8913
#Mann= 3 , 0 , 0
8646.595  0.0459       08646.595  0.0459       011353.31  0.0459       0
#XS Ineff= 2 , 0
       0                10164.28       0
Bank Sta=8646.595,11353.31
Exp/Cntr=0.3,0.1

Type RM Length L Ch R = 1 ,61054.72,608.518900,608.518900,608.518900
XS GIS Cut Line= 6
903959.954849723 815744.80631301903875.363084026815479.251516054
903850.000749727815360.481279058903830.399244028815315.088318492
903533.046993714 814732.77349496903457.065237566814471.792680366
#Sta/Elev= 30
9596.905435.50989617.744433.12039712.438406.92819765.046394.81119817.447386.8477
9879.999374.30069900.567367.32189931.418351.1676 9954.31334.68449962.155331.5475
9992.565325.9908 10024.9326.501310046.69336.363110102.44 333.402 10170.2335.1107
10237.57334.219710304.94340.456310322.33 340.47810361.08 337.84710428.45 339.067
10439.68336.7348 10686.7335.612410791.85348.123110823.09349.114710864.76347.3994
10885.59342.7742   10896343.150210906.42 346.67910916.83347.778310972.25349.5304
#Mann= 3 , 0 , 0
9596.905    0.04       09596.905    0.04       010972.25    0.04       0
#XS Ineff= 2 , 0
       0                10260.67       0
Bank Sta=9596.905,10972.25
Exp/Cntr=0.3,0.1

Type RM Length L Ch R = 1 , 60446.2,213.889000,213.889000,213.889000
XS GIS Cut Line= 3
 904133.45861398815222.852858072904045.615318342815060.342761142
903479.026061476814449.831856457
#Sta/Elev= 30
 9580.98345.01389635.376344.17329703.581341.56699825.418340.03829841.215338.0863
9868.501332.57739898.921 331.7179936.716328.69579964.002319.54359972.423318.0516
10001.82317.217710045.86329.5621 10059.5335.003110073.14334.987710086.79336.8827
10114.07335.091910141.36334.291110195.93334.553610236.86333.204610266.43334.4251
   10346335.337810359.65336.352110400.57334.529410428.14335.832210455.15338.7601
10472.24 337.80110486.94342.652610496.08344.516410516.34346.577910598.63348.5679
#Mann= 3 , 0 , 0
 9580.98    0.04       0 9580.98    0.04       010598.63    0.04       0
#XS Ineff= 2 , 0
       0                               0
Bank Sta=9580.98,10598.63
Exp/Cntr=0.3,0.1

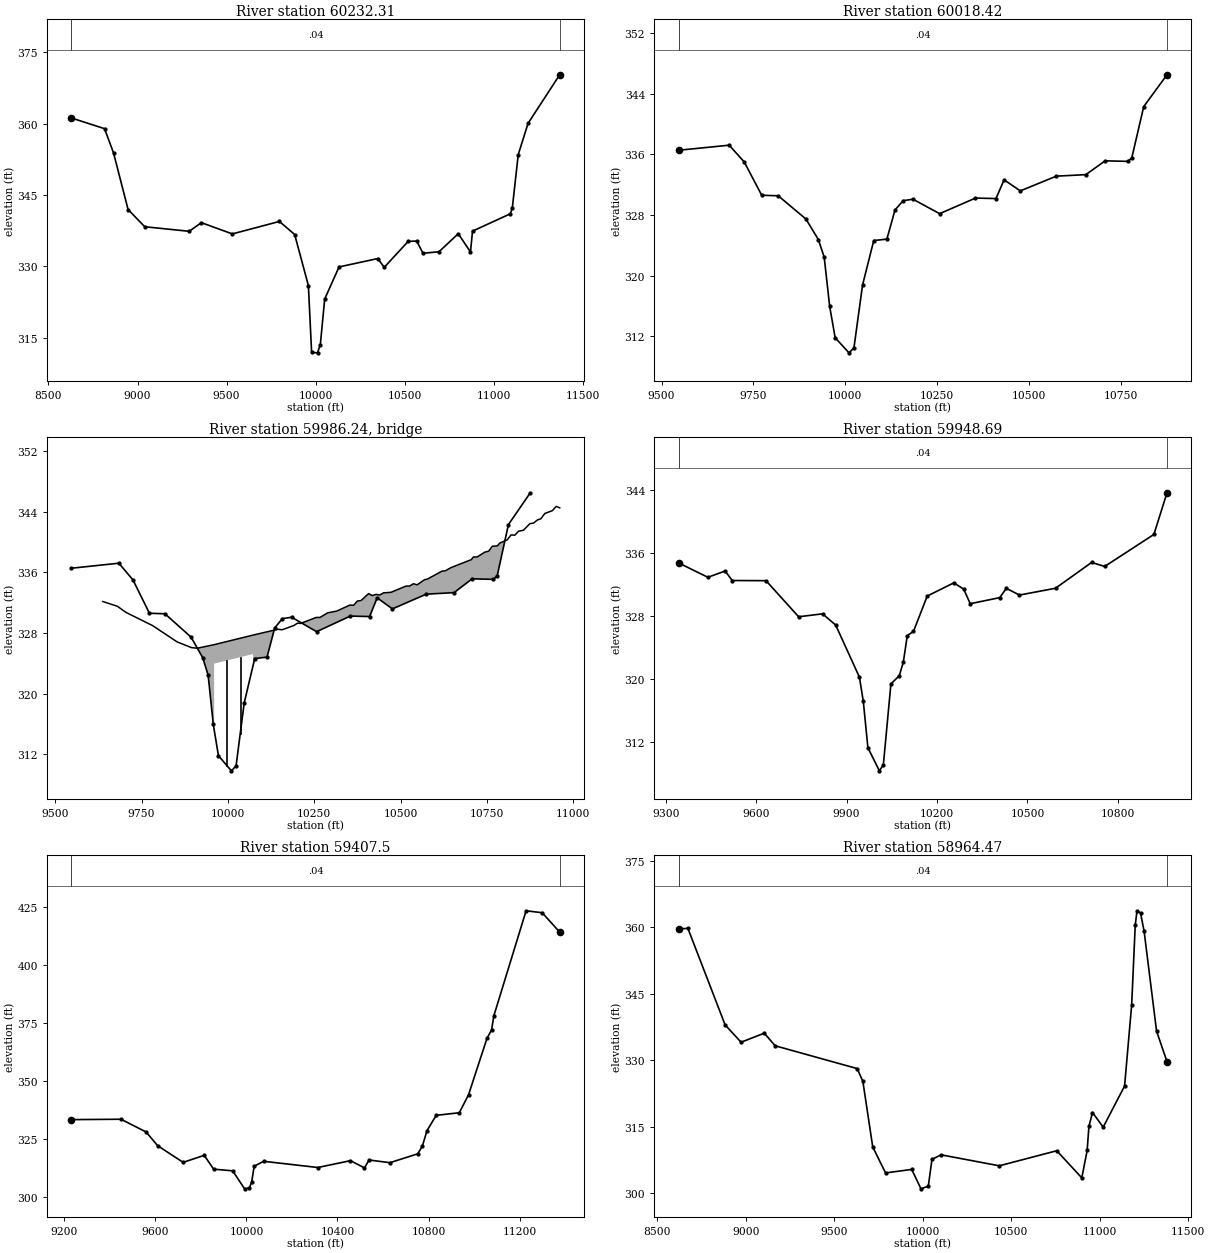
Type RM Length L Ch R = 1 ,60232.31,213.889000,213.889000,213.889000
XS GIS Cut Line= 6
904761.919452481815850.208473967904716.208471865 815518.71801264
 904618.55594697815281.480430426904071.467559318814785.102013896
903636.303418969814158.302061219903353.380994932813582.028943723
#Sta/Elev= 30
8628.621361.20958814.797358.96618865.329353.85858947.068341.94449040.721338.3259
9289.914337.36849358.872 339.1819532.691 336.8169797.007339.44079882.772336.6902
9959.792325.94559977.934311.887310011.14311.788810026.95313.542910051.41323.1176
10132.01329.866810349.18331.6299 10386.1329.791110520.02335.232710568.19335.3236
 10603.6332.741910693.31333.062310801.67336.858910870.37333.018310881.71337.4025
 11094.5341.0552 11105.5342.359911138.51353.502811193.52360.071111371.41370.3054
#Mann= 3 , 0 , 0
8628.621    0.04       08628.621    0.04       011371.41    0.04       0
#XS Ineff= 2 , 0
       0                               0
Bank Sta=8628.621,11371.41
Exp/Cntr=0.3,0.1

Type RM Length L Ch R = 1 ,60018.42,69.732300,69.732300,69.732300
XS GIS Cut Line= 6
904416.427896873815000.414673725 904381.93266681814803.295540516
904257.959592605814657.657268878904144.819117118814555.349392107
903728.365877556814365.177103521903426.450073354814240.956810315
#Sta/Elev= 30
9546.651336.52439684.076337.18979725.013334.98169772.592330.58979817.533330.5208
9893.014327.45119926.775324.74839942.622322.42569957.531315.93899972.441311.8127
10010.06309.815110023.54  310.4610046.99318.747510077.47324.618810113.19324.8055
10135.38328.656810157.58329.876610184.28330.066310256.75328.161710354.33330.2188
10410.21330.153910432.14332.625310476.29331.166610574.31333.108210654.64333.3062
 10707.2335.128310768.95335.057210779.76  335.53 10812.2342.278810875.52346.4727
#Mann= 3 , 0 , 0
9546.651    0.04       09546.651    0.04       010875.52    0.04       0
#XS Ineff= 2 , 0
       0                10113.57       0
Bank Sta=9546.651,10875.52
Exp/Cntr=0.3,0.1

Type RM Length L Ch R = 3 ,59986.24,,,
BEGIN DESCRIPTION:
END DESCRIPTION:
Bridge Culvert--1,0,-1,-1, 0
Deck Dist Width WeirC Skew NumUp NumDn MinLoCord MaxHiCord MaxSubmerge Is_Ogee
23.547250,22.637800,2.6,0, 60, 60, , , 0.95, 0, 0,0,,
 9637.36 9679.85 9705.18 9781.91 9852.53 9894.28 9911.33 9960.01 9960.0110072.54
10072.5410144.8010156.5710190.8310201.6510210.3610255.7410266.5610288.9910315.20
10353.1010363.9210374.7410385.5610407.2010418.0110428.8310439.6510450.4710472.11
10515.3810526.2010537.0210547.8410569.4710577.2910620.1210629.3310645.3910704.78
10710.7810721.6810743.4710755.0810765.2710780.2310787.0710808.8610819.7610830.66
10841.5610855.6810874.2610885.1510896.0510905.9810917.8510939.6510950.5510960.69
  332.14  331.51  330.69  328.96  326.82  326.06  325.98  326.45  326.45  327.71
  327.71  328.48  328.41  328.97  329.29  329.25  330.04  330.04  330.65  330.88
  331.67  331.64  332.20  332.27  333.18  332.92  333.08  333.00  333.28  333.35
  334.17  334.18  334.48  334.34  335.02  335.09  336.15  336.18  336.60  337.66
  338.01  338.01  338.64  338.78  339.42  339.48  339.84  340.27  340.92  340.88
  341.41  341.53  342.40  342.48  342.89  343.04  343.75  344.12  344.68  344.49
 -667.86 -668.49 -669.31 -671.04 -673.18 -673.94 -674.02 -673.55  323.95  325.21
 -672.29 -671.52 -671.59 -671.03 -670.71 -670.75 -669.96 -669.96 -669.35 -669.12
 -668.33 -668.36 -667.80 -667.73 -666.82 -667.08 -666.92 -667.00 -666.72 -666.65
 -665.83 -665.82 -665.52 -665.66 -664.98 -664.91 -663.85 -663.82 -663.40 -662.34
 -661.99 -661.99 -661.36 -661.22 -660.58 -660.52 -660.16 -659.73 -659.08 -659.12
 -658.59 -658.47 -657.60 -657.52 -657.11 -656.96 -656.25 -655.88 -655.32 -655.51
 9637.36 9679.85 9705.18 9781.91 9852.53 9894.28 9911.33 9963.92 9963.9210076.46
10076.4610144.8010156.5710190.8310201.6510210.3610255.7410266.5610288.9910315.20
10353.1010363.9210374.7410385.5610407.2010418.0110428.8310439.6510450.4710472.11
10515.3810526.2010537.0210547.8410569.4710577.2910620.1210629.3310645.3910704.78
10710.7810721.6810743.4710755.0810765.2710780.2310787.0710808.8610819.7610830.66
10841.5610855.6810874.2610885.1510896.0510905.9810917.8510939.6510950.5510960.69
  332.14  331.51  330.69  328.96  326.82  326.06  325.98  326.49  326.49  327.75
  327.75  328.48  328.41  328.97  329.29  329.25  330.04  330.04  330.65  330.88
  331.67  331.64  332.20  332.27  333.18  332.92  333.08  333.00  333.28  333.35
  334.17  334.18  334.48  334.34  335.02  335.09  336.15  336.18  336.60  337.66
  338.01  338.01  338.64  338.78  339.42  339.48  339.84  340.27  340.92  340.88
  341.41  341.53  342.40  342.48  342.89  343.04  343.75  344.12  344.68  344.49
 -667.86 -668.49 -669.31 -671.04 -673.18 -673.94 -674.02 -673.51  323.99  325.25
 -672.25 -671.52 -671.59 -671.03 -670.71 -670.75 -669.96 -669.96 -669.35 -669.12
 -668.33 -668.36 -667.80 -667.73 -666.82 -667.08 -666.92 -667.00 -666.72 -666.65
 -665.83 -665.82 -665.52 -665.66 -664.98 -664.91 -663.85 -663.82 -663.40 -662.34
 -661.99 -661.99 -661.36 -661.22 -660.58 -660.52 -660.16 -659.73 -659.08 -659.12
 -658.59 -658.47 -657.60 -657.52 -657.11 -656.96 -656.25 -655.88 -655.32 -655.51
Pier Skew, UpSta & Num, DnSta & Num=  ,9997.02, 2 ,10000.93, 2 , 0 , 0 , 0 ,,
    3.00    3.00
 -673.14  326.86
    3.00    3.00
 -673.09  326.91
Pier Skew, UpSta & Num, DnSta & Num=  ,10035.53, 2 ,10039.44, 2 , 0 , 0 , 0 ,,
    3.00    3.00
 -672.71  327.29
    3.00    3.00
 -672.66  327.34
BR Coef=-1 , 0 , 0 ,, 0 ,,,0.8,0,1,0,
WSPro=,,,, 1 ,,,, 0 ,,,, 0 ,,,,-1 ,-1 ,-1 , 0 , 0 , 0 , 0 , 0
BC Design=,, 0 ,, 0 ,,,,,,

Type RM Length L Ch R = 1 ,59948.69,541.189200,541.189200,541.189200
XS GIS Cut Line= 6
904705.135682705815042.774102014904621.059654116814880.146566313
904433.789007984814750.414673725904359.136230207814679.234118169
904188.997341318814483.053562614903415.055156378814143.662167738
#Sta/Elev= 30
9343.331334.69689440.216332.87939497.374333.67779520.898332.47269632.934332.4505
  9741.1327.87589820.385328.24489864.036326.82399942.749320.21519955.613317.1511
9970.876311.267310008.93308.334910022.17309.099610047.19319.360710075.12320.4049
10088.35322.134210101.59325.492910121.97 326.01310167.67330.503810255.91332.1754
10288.55331.378210310.31329.530610408.22330.303210429.98331.480110473.48330.6281
10593.11331.490310712.75 334.76310756.25334.259410919.39338.312610962.84343.5984
#Mann= 3 , 0 , 0
9343.331    0.04       09343.331    0.04       010962.84    0.04       0
#XS Ineff= 2 , 0
       0                10112.63       0
Bank Sta=9343.331,10962.84
Exp/Cntr=0.3,0.1

Type RM Length L Ch R = 1 , 59407.5,443.035700,443.035700,443.035700
XS GIS Cut Line= 6
904839.988507727815042.774102014904836.172662786814805.797366222
904809.208703319814606.318596254904671.987467719814115.119343475
904601.037605178813815.050482541904453.493992152812938.831360906
#Sta/Elev= 30
9230.658333.55599448.523333.72519559.017328.2293 9609.67322.3357 9721.69315.1341
9814.342318.16589855.787312.20229939.417311.48699991.795303.723810012.75304.1244
10023.23306.773210033.71313.469710075.53315.596410313.56312.921210457.06315.8703
10518.39312.761110538.78316.150810630.55314.998410752.64318.817710772.96322.1323
10793.28328.809810833.91335.410710935.32336.518810975.83 344.26711056.87368.5567
11077.13372.240611087.26 378.36311228.79423.571211299.51422.725611376.47414.3797
#Mann= 3 , 0 , 0
9230.658    0.04       09230.658    0.04       011376.47    0.04       0
#XS Ineff= 2 , 0
       0                10086.45       0
Bank Sta=9230.658,11376.47
Exp/Cntr=0.3,0.1

Type RM Length L Ch R = 1 ,58964.47,443.035700,443.035700,443.035700
XS GIS Cut Line= 6
904839.964963677 815647.02345697904858.081220802815303.879756612
904900.423753251 815050.10035628905141.738750615814362.834947552
 905258.91332839813891.201192229905386.526754939812956.384609053
#Sta/Elev= 30
8619.989359.6645 8672.04359.80348882.293337.98378972.624334.05369103.898 336.105
9164.954333.25539628.924328.09669661.065 325.1889716.778310.37839789.258304.5013
9937.164 305.297 9989.36300.904210030.88301.510110051.63307.586810103.49308.5921
10432.22306.114810756.94309.520410898.48303.3774 10928.7309.590310938.77 315.032
10958.92318.162711019.35314.854711140.23324.142211180.43342.553311200.52  360.55
11210.57363.779711230.67363.247311250.77359.127811321.11336.556411380.01329.6732
#Mann= 3 , 0 , 0
8619.989    0.04       08619.989    0.04       011380.01    0.04       0
#XS Ineff= 2 , 0
       0                10085.86       0
Bank Sta=8619.989,11380.01
Exp/Cntr=0.3,0.1

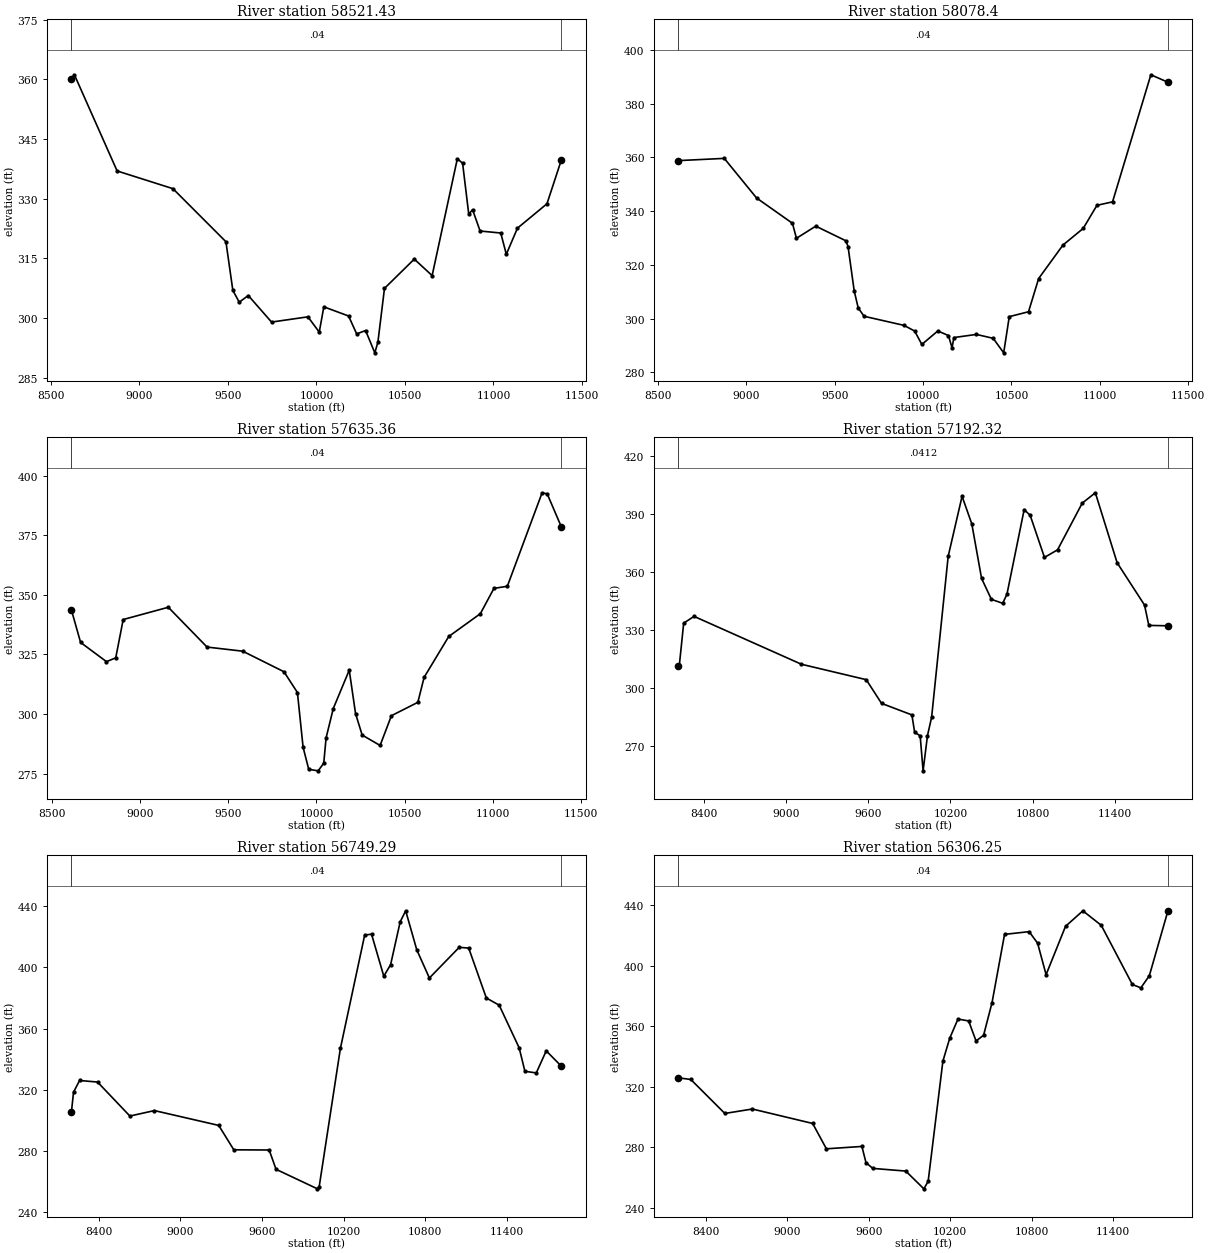
Type RM Length L Ch R = 1 ,58521.43,443.035700,443.035700,443.035700
XS GIS Cut Line= 6
904853.980898684815601.558443034904984.683055455815016.722904961
905503.266629241814558.931693994905764.009715185  814222.8681999
905980.436333567813809.543225487906154.967795309813266.731669836
#Sta/Elev= 30
8616.462360.19848633.061361.16178874.305336.96789189.584332.51289488.973319.1682
    9528306.93659564.124303.95519615.161305.63559746.764298.95449952.112300.2729
10016.17 296.43410042.01302.788510181.84300.481110227.64295.9724 10277.9296.8285
10329.98291.215410347.46293.8968 10384.6 307.42610552.94314.793910653.86310.6487
10796.17340.036510825.88338.920310860.64326.105610882.32327.2115 10924.8321.8584
11041.47321.358311072.88316.0066 11135.7 322.57411302.41328.710411383.56339.7103
#Mann= 3 , 0 , 0
8616.462    0.04       08616.462    0.04       011383.56    0.04       0
#XS Ineff= 2 , 0
       0                10050.04       0
Bank Sta=8616.462,11383.56
Exp/Cntr=0.3,0.1

Type RM Length L Ch R = 1 , 58078.4,443.035600,443.035600,443.035600
XS GIS Cut Line= 6
904863.237983334 815835.05208901905078.188356524 815071.99749481
  905335.0198799814909.943996608905771.165546993814896.078144263
906002.249871777814782.248770859906475.549824063813964.763302035
#Sta/Elev= 30
8614.517358.76238875.574359.5994 9058.42344.86089261.248335.44929283.902329.8695
9393.272334.38129563.931328.92249575.759326.79079610.712310.24059633.291303.9476
9666.425300.84719892.674297.45459952.747295.33619993.133290.3684 10083.7295.3903
10143.84293.662610164.01289.114410174.57 292.92910301.85294.094810396.66292.6435
10456.21287.241210487.72300.709110596.63302.525110653.95314.891110791.57 327.355
10905.86333.528610983.76342.130611071.98 343.42711288.67390.706811385.36387.9288
#Mann= 3 , 0 , 0
8614.517    0.04       08614.517    0.04       011385.36    0.04       0
#XS Ineff= 2 , 0
       0                10088.01       0
Bank Sta=8614.517,11385.36
Exp/Cntr=0.3,0.1

Type RM Length L Ch R = 1 ,57635.36,443.035700,443.035700,443.035700
XS GIS Cut Line= 6
905316.437226393816474.503734456905493.489566737815959.186782195
 905785.04345607815353.552031174905890.170367498815085.712308692
906235.234741843814590.833167412906503.532028143813980.306775911
#Sta/Elev= 30
8611.307343.55868663.056330.01858809.688 321.961 8862.29323.55838904.556 339.625
  9160.3344.77129380.024328.07749582.215326.34819816.089317.7285 9892.36309.0129
 9924.58286.04639956.526276.802910009.73276.159210041.64279.345810054.94289.9821
10095.66302.280410186.21318.3855   10222 300.16910259.46291.174410361.19286.8084
10425.32299.286910575.14304.894710610.71315.383810750.35332.510410929.54342.0715
11006.63352.691811082.52353.586311279.65392.793811308.76392.329211388.62 378.513
#Mann= 3 , 0 , 0
8611.307    0.04       08611.307    0.04       011388.62    0.04       0
#XS Ineff= 2 , 0
       0                10077.07       0
Bank Sta=8611.307,11388.62
Exp/Cntr=0.3,0.1

Type RM Length L Ch R = 1 ,57192.32,443.035700,443.035700,443.035700
XS GIS Cut Line= 6
905790.481575241817062.695906227906172.125489129815914.688946777
906250.214830267815448.096453422906226.479478174815231.375930757
906312.164626913814785.383052244 906703.20877899813631.908767132
#Sta/Elev= 30
  8210.9311.49888219.211311.28298251.611333.5199 8327.21337.04099111.786312.2385
9585.115304.26069696.811291.98469918.604286.0044 9938.63277.04919979.081275.1679
10000.47 257.04510032.37275.251510062.79284.845410183.67 368.129 10285.2399.2317
10356.28384.913310427.52356.724210499.18 345.86410581.71343.800210612.95348.4923
10738.63392.299410782.48389.395210886.97367.575510982.56371.486611163.11395.6951
 11258.7401.041211417.77364.815411617.93342.895511649.41332.355711789.08332.1614
#Mann= 3 , 0 , 0
  8210.9  0.0412       0  8210.9  0.0412       011789.08  0.0412       0
#XS Ineff= 2 , 0
       0                10201.95       0
Bank Sta=8210.9,11789.08
Exp/Cntr=0.3,0.1

Type RM Length L Ch R = 1 ,56749.29,443.035700,443.035700,443.035700
XS GIS Cut Line= 6
906416.365972642816958.724723877906771.723462659815822.405531677
 906754.97398727815426.030424202906511.247398899815125.564567732
906454.520150965814818.718890833906800.727896902813568.880707709
#Sta/Elev= 30
8198.025305.74038213.246318.40818257.608326.0403 8389.72 325.0278627.818302.8031
 8808.13306.38069281.384 296.6949392.276280.7532 9652.71280.62019703.022268.0092
10007.64255.2466 10020.2256.466410176.44346.956110355.26421.0721 10405.7421.6351
10495.78394.179310545.91401.7119 10616.3429.678510656.87436.930710738.43 411.424
 10831.3393.003211050.59413.029211120.48 412.56711250.26 379.94411344.83375.2423
11491.96347.333311533.99332.048811617.69330.987811690.91345.404111801.91335.4293
#Mann= 3 , 0 , 0
8198.025    0.04       08198.025    0.04       011801.91    0.04       0
#XS Ineff= 2 , 0
       0                               0
Bank Sta=8198.025,11801.91
Exp/Cntr=0.3,0.1

Type RM Length L Ch R = 1 ,56306.25,431.000000,431.000000,431.000000
XS GIS Cut Line= 6
906474.561653609816888.893190917906747.472142857816175.535953507
906869.942980403815287.760230987907074.428607305815097.866358025
907188.760932296814898.882394155907606.072244104813533.389590076
#Sta/Elev= 30
8196.178325.76198289.432324.69228540.384302.20478742.806305.14159187.012295.5921
 9288.31278.82899549.799280.39419579.873 269.7039629.995265.87659872.875264.1053
10006.23252.362210037.76257.332510146.33336.817910196.65351.945410257.39364.6229
10335.93363.378310390.55350.115810446.04353.9093 10508.3375.518110600.47420.6138
10781.13422.415510843.73414.827310906.33393.985811049.43425.933911177.24436.1697
11312.64426.609711541.79387.479311604.29 385.24411666.79393.285511803.87436.2119
#Mann= 3 , 0 , 0
8196.178    0.04       08196.178    0.04       011803.87    0.04       0
#XS Ineff= 2 , 0
       0                               0
Bank Sta=8196.178,11803.87
Exp/Cntr=0.3,0.1