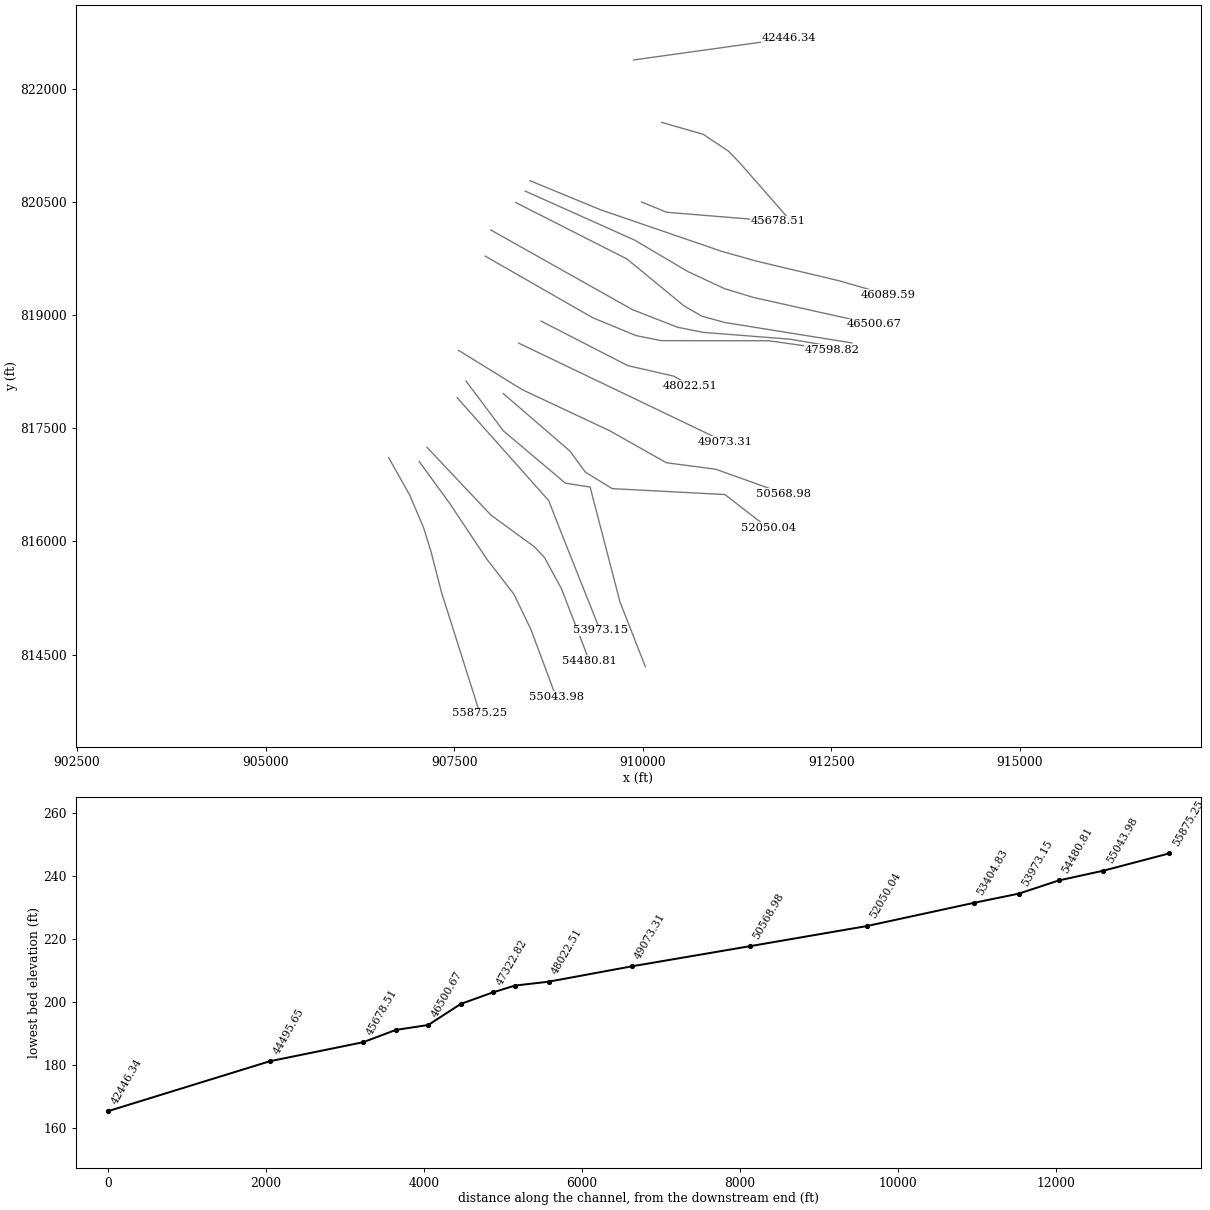
HEC-RAS study 16296_ras.prj: 16296

--- 16296_ras.g01 (geometry) --- (continued)

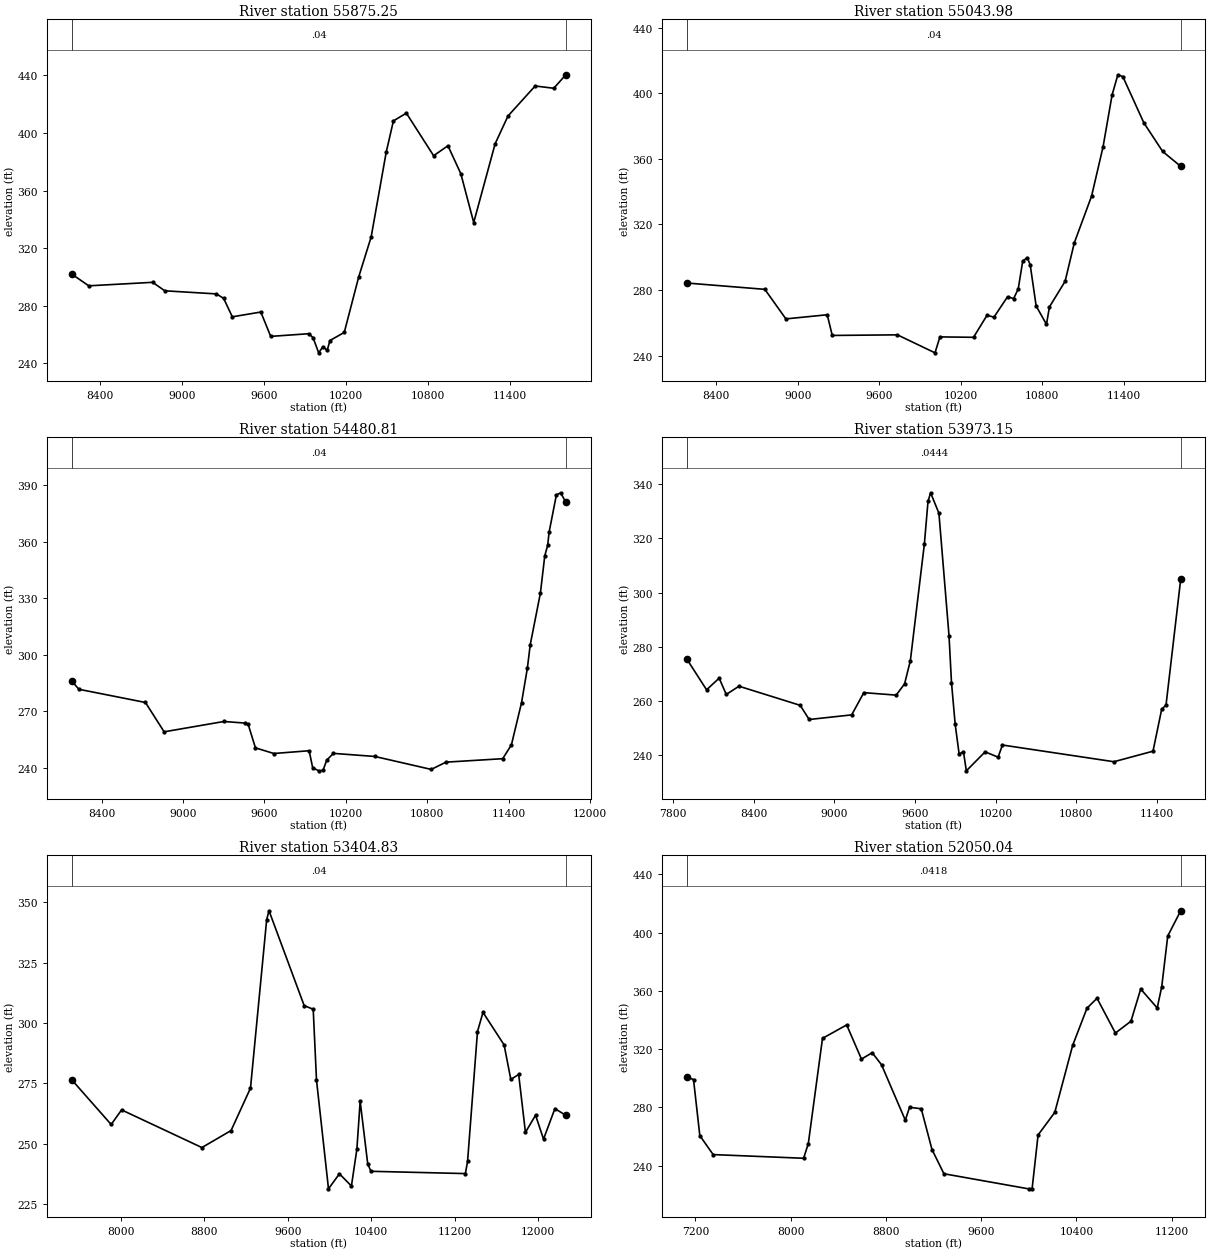
Type RM Length L Ch R = 1 ,55875.25,831.270500,831.270500,831.270500
XS GIS Cut Line= 6
906631.052173327817111.801044754906909.581139161816615.792119409
907093.127180157816184.642790202907192.623378034815865.389408417
907329.599438133815331.617061818907840.387694701813720.554867431
#Sta/Elev= 30
8193.145301.90238318.005293.71698785.263296.15028873.961290.25669251.782288.0934
 9304.54284.97479367.807272.15699576.257275.4844 9648.66258.55729927.455260.4124
9958.331257.65829999.506247.112310030.35251.345110061.66248.818510081.99255.6915
10186.63261.319110292.32299.959610383.31327.732910493.29386.6311   10546408.4058
10640.65413.814110840.03384.184510944.76391.123311039.02371.679911133.23337.7332
11290.03392.5437 11384.1411.832711582.71432.6746 11718.6431.099311806.87440.4746
#Mann= 3 , 0 , 0
8193.145    0.04       08193.145    0.04       011806.87    0.04       0
#XS Ineff= 2 , 0
       0 9808.86                       0
Bank Sta=8193.145,11806.87
Exp/Cntr=0.3,0.1

Type RM Length L Ch R = 1 ,55043.98,563.169600,563.169600,563.169600
XS GIS Cut Line= 6
907035.980111465817059.845304669907442.969286781816500.743821038
907929.249123115815770.158367562908292.921327442815299.086327694
908519.432961625814826.860811594908849.728719764813940.132976975
#Sta/Elev= 30
8181.909284.24438757.844280.37338912.671262.34639216.996264.86749253.953252.2447
9733.221252.6131   10010241.632710046.27251.3563 10293.5251.107610392.96264.5646
10443.86263.391610543.63275.836510588.73274.742110622.45280.638310655.45297.5684
10688.45299.767910710.45295.383410754.28270.2143 10830.3259.030710852.03269.6551
10967.33285.245111035.23308.785111162.06337.231811246.65 367.32811313.14398.9936
11355.67411.283311392.09410.177111547.06381.932611685.28364.488811818.05355.4228
#Mann= 3 , 0 , 0
8181.909    0.04       08181.909    0.04       011818.05    0.04       0
#XS Ineff= 2 , 0
       09694.388                       0
Bank Sta=8181.909,11818.05
Exp/Cntr=0.3,0.1

Type RM Length L Ch R = 1 ,54480.81,507.666600,507.666600,507.666600
XS GIS Cut Line= 6
907139.281094665 817247.69417897907986.611996417816349.982424217
908561.263726488815930.510060504 908697.61257036815785.550172976
908921.092122739815375.650342742909290.062260108814419.840810826
#Sta/Elev= 30
8179.832286.18078233.031281.76718723.187  274.78 8860.85259.22429300.885264.6961
9452.955263.88199479.985 263.1699533.624250.71429669.119247.73349929.246249.2003
9955.283 240.15610001.03238.545310031.12238.730810059.04244.247610107.81247.8038
10413.08246.161410828.73239.293910937.11243.1504 11355.1244.982611419.21252.3047
11493.63274.575611536.75292.939411558.13305.485211632.93332.790311664.98352.4921
11686.35358.037411697.04365.059111750.47384.762111782.53385.9082 11820.1380.8208
#Mann= 3 , 0 , 0
8179.832    0.04       08179.832    0.04       0 11820.1    0.04       0
#XS Ineff= 2 , 0
       09858.453                       0
Bank Sta=8179.832,11820.1
Exp/Cntr=0.3,0.1

Type RM Length L Ch R = 1 ,53973.15,568.316200,568.316200,568.316200
XS GIS Cut Line= 4
907538.810563592817906.098987798908752.352230258816542.383710021
908947.664730258816043.251765576909433.775841369814823.633710021
#Sta/Elev= 30
7901.329 275.6518050.048264.18958143.751268.4839 8196.45262.47318290.998265.5155
8746.127258.47358813.057 253.2559129.094254.9557 9219.35263.14199460.032  262.23
9522.522266.3864 9565.33274.8946 9669.77317.96969696.542333.54849715.757336.7527
9777.699329.24379852.867284.13119871.295 266.8429898.737251.44439928.035240.5537
 9960.25241.36159981.727234.346310121.33241.343610217.97239.376810250.19 243.852
11079.06237.700911369.72241.583311434.31257.0406 11466.6258.593411575.73304.9163
#Mann= 3 , 0 , 0
7901.329  0.0444       07901.329  0.0444       011575.73  0.0444       0
#XS Ineff= 2 , 0
       09760.413                       0
Bank Sta=7901.329,11575.73
Exp/Cntr=0.3,0.1

Type RM Length L Ch R = 1 ,53404.83,1354.794000,1354.794000,1354.794000
XS GIS Cut Line= 6
907655.998063592818127.453154465 908151.70780275 817466.53831421
908973.706396925816773.286487798909301.831396925816721.203154465
909698.164656876815197.024389327910034.582123651814338.806514607
#Sta/Elev= 30
7530.424276.54657908.497258.03068008.499264.06628777.765 248.4959056.964255.5253
9243.096273.08059398.206342.80389420.497346.41059757.202307.18839843.813 305.686
9875.187276.44689990.226231.420710094.81237.644510209.85232.578610262.14247.8643
10293.51267.6331 10365.9241.763710396.91238.675711301.47237.7285 11322.4242.8287
11417.23296.455811470.01304.390711672.34290.932511736.54276.650511811.78278.7144
11876.53254.781311973.65261.870712049.79251.967312158.66264.587312263.39261.8277
#Mann= 3 , 0 , 0
7530.424    0.04       07530.424    0.04       012263.39    0.04       0
#XS Ineff= 2 , 0
       0 9850.14                       0
Bank Sta=7530.424,12263.39
Exp/Cntr=0.3,0.1

Type RM Length L Ch R = 1 ,52050.04,1481.060900,1481.060900,1481.060900
XS GIS Cut Line= 6
908150.789730258817960.786487798909033.646761569817199.201026722
909239.331396925816919.119821131909593.498063592816700.369821131
911088.289730258816622.244821131911661.206396925816179.536487798
#Sta/Elev= 30
7125.871300.83747184.258299.11177237.084260.62687349.064247.5689 8108.72245.0455
 8148.34255.04298267.637327.37388470.733336.60578594.802313.14428685.218317.5298
8763.518309.2191 8963.33271.16118998.591280.04219097.153279.03759187.276251.0559
9287.412234.41229998.381224.052610028.42224.203910078.49261.057710218.68276.5318
10368.89 322.54210489.05348.072210573.54354.917310727.82331.018610858.66339.1418
10940.43361.263411079.05348.240111116.96362.787811167.51397.645411276.46414.9762
#Mann= 3 , 0 , 0
7125.871  0.0418       07125.871  0.0418       011276.46  0.0418       0
#XS Ineff= 2 , 0
       09141.644                       0
Bank Sta=7125.871,11276.46
Exp/Cntr=0.3,0.1

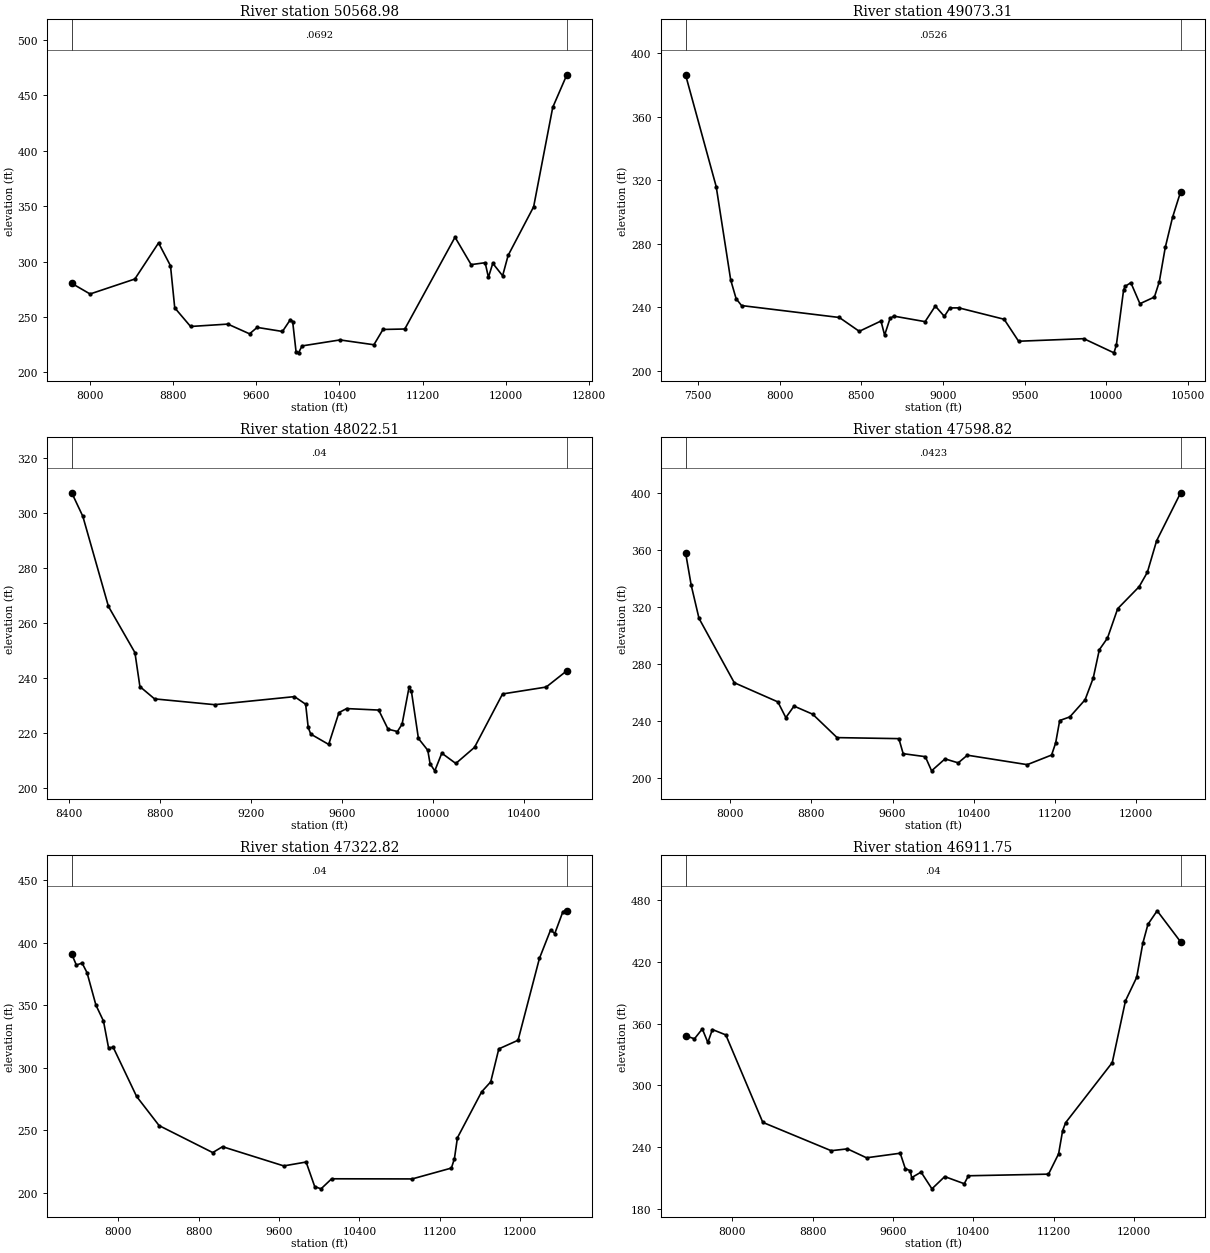
Type RM Length L Ch R = 1 ,50568.98,1495.663400,1495.663400,1495.663400
XS GIS Cut Line= 6
907558.670997007818533.241398005 908400.50176695 818013.44930308
909561.873097581817467.644799848910313.681607261817043.512599577
910965.051670849816958.133200577 911869.57820752816635.574504911
#Sta/Elev= 30
7827.615280.30588003.834270.71468433.997284.19818661.974316.74938776.683296.1294
8817.407258.22088969.571241.41699327.588243.56929536.594234.79589609.568240.5885
9852.503236.92419928.617247.58889950.644245.9032 9984.08218.003910007.07217.6567
10040.98223.896710405.46229.298410731.39 224.94610818.82238.737211028.24239.1331
11510.95321.898211665.56297.189811800.69298.906911831.97285.707611873.81298.3702
11968.39287.133212021.16305.460912266.43349.318212449.99438.973512585.61468.3317
#Mann= 3 , 0 , 0
7827.615  0.0692       07827.615  0.0692       012585.61  0.0692       0
#XS Ineff= 2 , 0
       09786.293                       0
Bank Sta=7827.615,12585.61
Exp/Cntr=0.3,0.1

Type RM Length L Ch R = 1 ,49073.31,1050.798300,1050.798300,1050.798300
XS GIS Cut Line= 2
908355.650841369818629.189265576911090.025841369817318.425376687
#Sta/Elev= 30
7423.105386.31437610.906315.88917699.623 257.1447732.892245.3354 7766.16241.0201
8364.998233.51268486.984224.80878620.059231.28738642.238222.41918675.507232.9109
8697.686234.38958890.233230.89388952.747240.71379008.195234.21929041.464239.5203
9096.912239.57139374.151232.40019462.868218.56089862.094220.175210046.93211.2563
10061.71216.200610106.06250.939710116.33253.192110150.42255.399110205.87242.1916
10294.59246.369710324.54256.014410361.13277.616510405.48 296.47110455.42312.7531
#Mann= 3 , 0 , 0
7423.105  0.0526       07423.105  0.0526       010455.42  0.0526       0
#XS Ineff= 2 , 0
       08800.464                       0
Bank Sta=7423.105,10455.42
Exp/Cntr=0.3,0.1

Type RM Length L Ch R = 1 ,48022.51,423.691700,423.691700,423.691700
XS GIS Cut Line= 4
908651.657785813818921.723987798909800.963341369818331.446210021
910408.602230258818192.557321132910634.296674702818067.557321132
#Sta/Elev= 30
8414.052307.36848462.776298.81548575.194266.09378691.431249.32118713.319236.9818
8777.547232.51989041.646230.41339391.861233.33959440.813 230.5839452.054  222.13
9463.296219.73419541.989215.97539586.956227.53629620.681228.99889761.508228.4554
 9802.54221.51819843.571220.66729864.087223.31059894.861236.78399905.119235.2698
9935.892218.13829976.924213.86359987.182208.9141 10007.7206.387310038.47212.8038
10100.02 209.06710182.08214.915810305.18234.310810496.74236.816210587.39242.7384
#Mann= 3 , 0 , 0
8414.052    0.04       08414.052    0.04       010587.39    0.04       0
#XS Ineff= 2 , 0
       09697.804                       0
Bank Sta=8414.052,10587.39
Exp/Cntr=0.3,0.1

Type RM Length L Ch R = 1 ,47598.82,276.000000,276.000000,276.000000
XS GIS Cut Line= 6
907910.827535785819783.361488603909335.969347755 818966.57344877
909912.570097883818728.687114902910247.777967818 818662.44324579
911668.682407144818661.349290159912507.951173048818542.968085827
#Sta/Elev= 30
7559.797358.35847615.549335.42757692.412312.17138040.265267.00068469.846253.5459
8548.366242.50398629.079250.60098812.886244.91549053.539228.48079662.528 227.763
9704.887217.20979923.047215.1108 9984.99205.163110117.36213.547410247.47210.7633
10337.49216.1463 10927.8209.503711167.82216.246811207.83224.695911247.85240.4706
11347.91243.033111498.12255.036211578.32270.281511638.55290.162511718.89298.3559
11819.41318.964712031.07334.403812111.95344.520412203.15366.633912440.15400.3097
#Mann= 3 , 0 , 0
7559.797  0.0423       07559.797  0.0423       012440.15  0.0423       0
#XS Ineff= 2 , 0
       0                10360.19       0
Bank Sta=7559.797,12440.15
Exp/Cntr=0.3,0.1

Type RM Length L Ch R = 1 ,47322.82,411.077000,411.077000,411.077000
XS GIS Cut Line= 6
907985.154588747820129.955281253909861.604576475819074.568877819
910459.367973051818840.546974765910800.969633798818772.336094355
911952.604302337818681.826723011912573.123804316 818576.26772661
#Sta/Elev= 30
7535.084 390.9267580.845382.15587638.268383.74667687.503376.02077776.085 350.048
7851.049337.34847901.924315.80787947.666316.37868180.875276.99918405.093253.6527
 8938.78 232.0589036.441236.76729646.264221.38429868.774224.49339954.535204.8196
10017.32203.032310122.94211.0745 10924.6210.9655 11315.3219.655611345.38227.1785
11375.45243.924611616.31280.648511706.85288.662811787.36315.041911979.09321.9716
12191.66387.422212303.54410.325412344.29407.296412425.97424.935612464.89425.5826
#Mann= 3 , 0 , 0
7535.084    0.04       07535.084    0.04       012464.89    0.04       0
#XS Ineff= 2 , 0
       0                10435.09       0
Bank Sta=7535.084,12464.89
Exp/Cntr=0.3,0.1

Type RM Length L Ch R = 1 ,46911.75,411.077100,411.077100,411.077100
XS GIS Cut Line= 6
908315.345098651820493.906481055909790.768978804819744.958683308
910547.925725636819122.750001661910780.712393803818987.988490044
911086.878836582818903.295319124912773.249824469818632.240532833
#Sta/Elev= 30
7532.549348.27747621.497345.32577699.663354.93237754.806341.74817800.163354.3436
7933.903349.10148302.586263.99758984.155236.42599146.135238.22269336.319229.5298
 9672.24 233.9739723.199218.91879772.296216.98319786.316210.24089880.142215.5933
9988.335199.321810115.63211.244710310.36204.303910352.26212.040311150.16213.6177
 11250.9233.3914 11291.2256.078811321.42263.770311785.65322.172611917.55 382.299
12029.25405.133112090.25438.298412141.26 456.68612233.15469.877612467.42439.5752
#Mann= 3 , 0 , 0
7532.549    0.04       07532.549    0.04       012467.42    0.04       0
#XS Ineff= 2 , 0
       0                10428.66       0
Bank Sta=7532.549,12467.42
Exp/Cntr=0.3,0.1

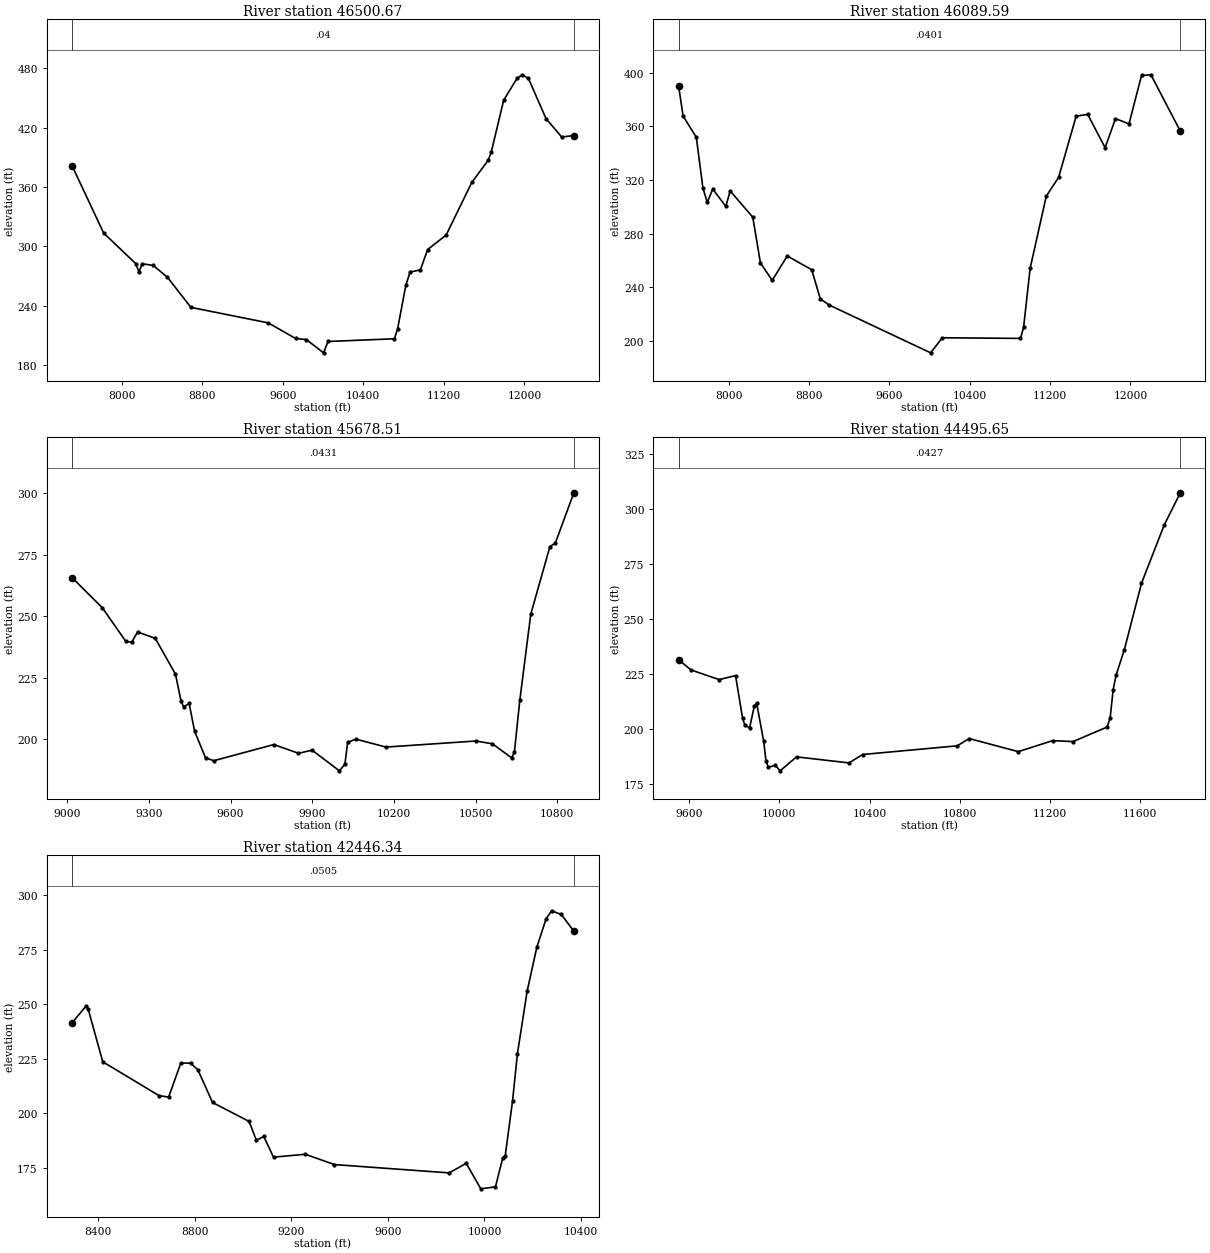
Type RM Length L Ch R = 1 ,46500.67,411.077000,411.077000,411.077000
XS GIS Cut Line= 6
908441.030424506820645.509196529909890.398331664 819996.31910432
910598.317006856819578.298444828911083.913351819 819352.02548978
911465.083623866819235.810408351913061.509971485818879.591676426
#Sta/Elev= 30
 7509.05381.49097822.442 313.6128140.041 282.8098172.863274.53238205.562282.5892
8314.557280.86728456.252268.93058688.539238.56929456.867222.8812 9727.68207.1661
9834.888206.0635 10005.7 192.648 10050.1204.109510709.77206.851210740.92216.8115
10823.69261.245510864.89274.225710967.42276.3971   11039296.897111222.63311.5142
11477.37364.613711640.41387.067111671.07395.381911793.75447.5386 11926.7469.7746
11978.02473.3492 12039.6469.666112214.65429.118412369.85410.580612490.98411.9588
#Mann= 3 , 0 , 0
 7509.05    0.04       0 7509.05    0.04       012490.98    0.04       0
#XS Ineff= 2 , 0
       0                10394.67       0
Bank Sta=7509.05,12490.98
Exp/Cntr=0.3,0.1

Type RM Length L Ch R = 1 ,46089.59,411.077100,411.077100,411.077100
XS GIS Cut Line= 6
908503.571345372 820783.60523491909441.541847924820397.173961741
 911049.30794917  819845.5450752911514.784124772819714.967308975
912599.597817212819457.260374969913254.951201942819268.947623333
#Sta/Elev= 30
7502.466390.43687547.816  367.697679.477351.8896 7744.97314.0705 7788.44303.2206
7842.777313.26717973.185300.33318016.632311.83548241.592292.23268317.848258.0475
8435.387245.15448584.564263.34798828.353253.03938912.925231.46578997.239226.9085
10012.05191.079810128.08202.320710906.47201.845610937.29210.059611002.63254.1757
11163.13307.960211286.31322.006711460.82367.665111575.57368.877911749.02 344.111
11852.18365.762411986.67361.849112111.17397.939212204.86398.473412497.54356.4324
#Mann= 3 , 0 , 0
7502.466  0.0401       07502.466  0.0401       012497.54  0.0401       0
#XS Ineff= 2 , 0
       0                10402.18       0
Bank Sta=7502.466,12497.54
Exp/Cntr=0.3,0.1

Type RM Length L Ch R = 1 ,45678.51,1182.867200,1182.867200,1182.867200
XS GIS Cut Line= 3
909982.426901317820502.028610367910317.569844351 820364.67494519
911792.748208361820243.803719833
#Sta/Elev= 30
9018.172265.74769129.026253.54219215.484239.84069237.098239.47849258.713243.6592
9323.556241.07549397.858226.49819417.925215.73579427.959213.16279448.026214.5783
9468.093203.28339508.227 192.4719538.327191.30359759.065197.87779849.366 194.334
9899.534195.57699999.869187.187410019.94189.904410029.97198.772810060.07200.0907
10170.44196.847510501.54199.326310561.75198.160410631.98192.482310642.01194.6662
10662.08215.916310702.21250.862910772.45278.337310792.52279.852410860.49300.2729
#Mann= 3 , 0 , 0
9018.172  0.0431       09018.172  0.0431       010860.49  0.0431       0
#XS Ineff= 2 , 0
       0                               0
Bank Sta=9018.172,10860.49
Exp/Cntr=0.3,0.1

Type RM Length L Ch R = 1 ,44495.65,2049.311600,2049.311600,2049.311600
XS GIS Cut Line= 5
910251.896820889821555.775121313910800.147612537821399.132037985
911136.197688811821175.061569739911284.539647203 821021.22546474
911968.560899789 820241.05664653
#Sta/Elev= 30
9553.029231.58799608.258226.92619733.059222.53939805.861224.36819837.061205.0046
9847.461201.75589868.262200.67929889.062210.53769899.462211.86549930.662194.5545
9941.063185.43419951.463182.79049982.663183.586110003.46181.138410076.26187.4728
10309.34184.739810369.43 188.54910789.01192.4942 10842.2195.793211060.07189.8447
11211.76194.841811302.77 194.42511453.97201.031811467.27205.238411480.57217.9921
11493.87224.6866 11530.3236.154611606.14266.252411706.66292.6301 11778.4 307.329
#Mann= 3 , 0 , 0
9553.029  0.0427       09553.029  0.0427       0 11778.4  0.0427       0
#XS Ineff= 2 , 0
       0                               0
Bank Sta=9553.029,11778.4
Exp/Cntr=0.3,0.1

Type RM Length L Ch R = 1 ,42446.34,776.551200,776.551200,776.551200
XS GIS Cut Line= 2
909879.132056435822384.394316309911936.423723102822670.852649642
#Sta/Elev= 30
8293.197241.49018349.604249.0269  8359.7247.87158420.279223.61018652.498208.1221
8692.884207.39178743.366223.03048783.752223.00398814.041219.9163 8874.62 204.923
9026.067 196.2179056.357187.49639086.646  189.359127.032179.81049258.286181.1567
9379.444176.41479853.978172.60369924.654176.99239985.232165.274210045.81166.1981
 10076.1179.5502 10086.2 180.44310116.49205.578410136.68227.299210177.07256.1034
10217.45276.385210255.39289.213910278.03292.949210318.42291.248710370.34283.5825
#Mann= 3 , 0 , 0
8293.197  0.0505       08293.197  0.0505       010370.34  0.0505       0
#XS Ineff= 2 , 0
       0                               0
Bank Sta=8293.197,10370.34
Exp/Cntr=0.3,0.1