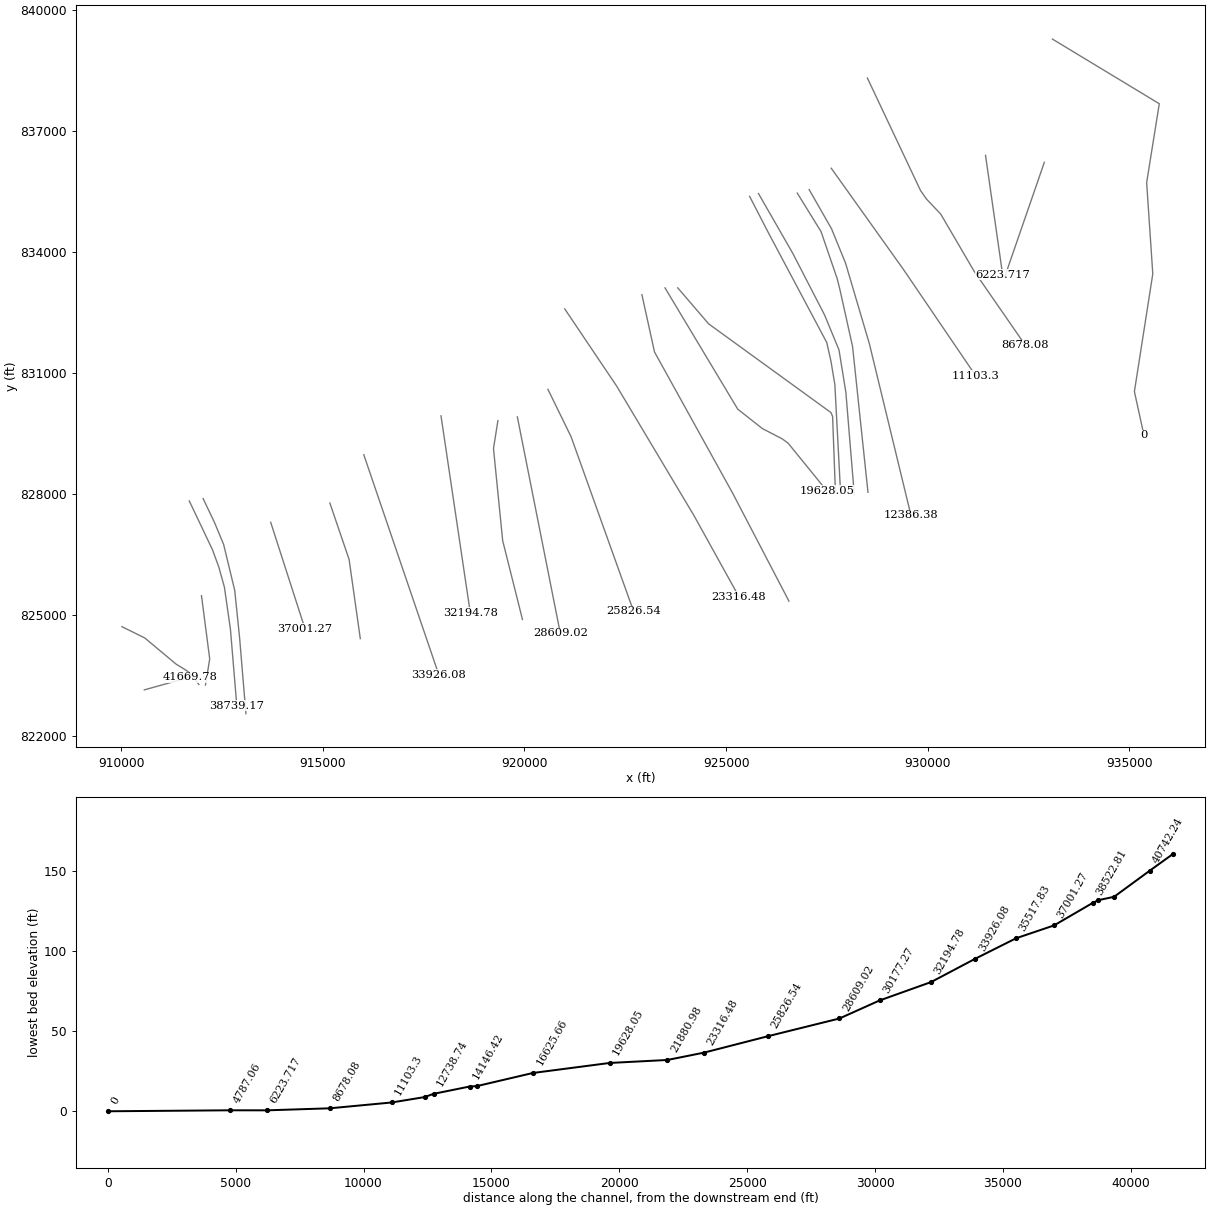
HEC-RAS study 16296_ras.prj: 16296

--- 16296_ras.g01 (geometry) --- (continued)

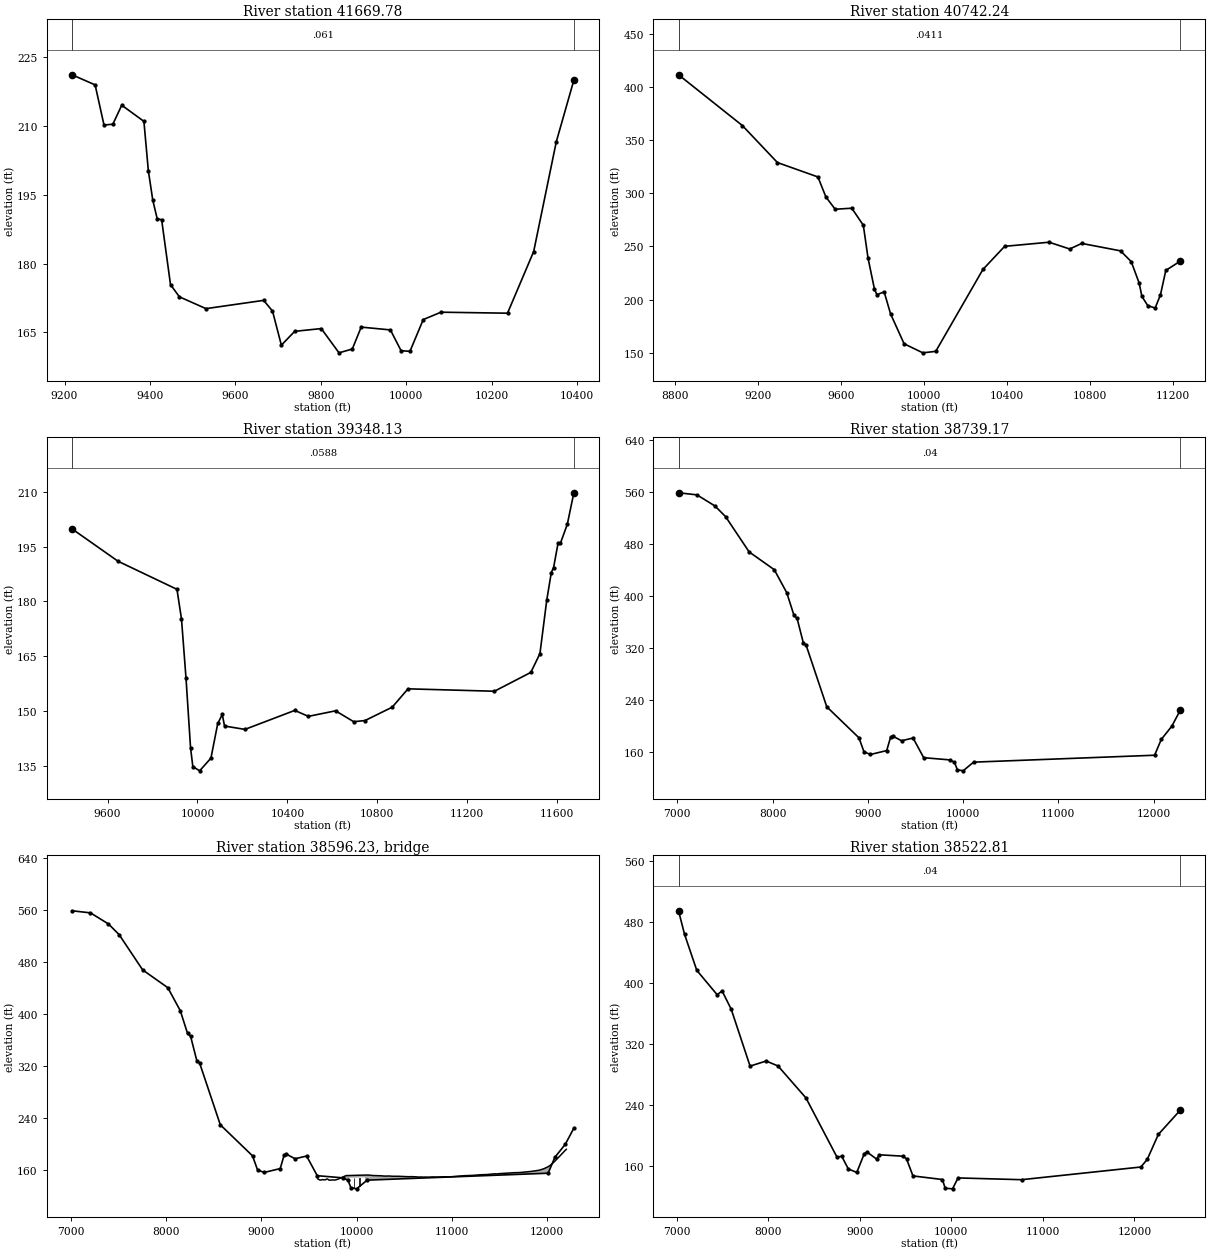
Type RM Length L Ch R = 1 ,41669.78,927.540800,927.540800,927.540800
XS GIS Cut Line= 2
910572.986225438823144.995260038911704.640001031823460.241668953
#Sta/Elev= 30
9217.575221.1396 9271.57218.93329292.331210.18469313.093210.36819333.854214.5118
9385.758210.98649396.139 200.2359406.519193.8225  9416.9 189.7429427.281189.5458
9448.043175.40359468.804172.75099531.089170.17519666.039171.9755  9686.8169.6529
9707.562 162.2129738.704 165.2259800.988165.82969842.511160.54099873.654161.3773
9894.415166.14819962.878165.53819987.842160.9954 10008.6160.874510039.75167.7935
10081.27169.397410236.98169.181610298.26182.621910351.17206.534410392.32219.9707
#Mann= 3 , 0 , 0
9217.575   0.061       09217.575   0.061       010392.32   0.061       0
#XS Ineff= 2 , 0
       0                               0
Bank Sta=9217.575,10392.32
Exp/Cntr=0.3,0.1

Type RM Length L Ch R = 1 ,40742.24,1394.114000,1394.114000,1394.114000
XS GIS Cut Line= 6
910018.020945324824710.783205198910582.257056435 824433.00542742
911363.507056435823781.963760753911632.604278657823617.033205198
911754.132056435823504.185982975911926.499477001823278.673542025
#Sta/Elev= 30
 8818.88411.28889126.302363.52249294.798 328.7769489.718315.24169528.136 296.397
9572.656284.90019652.695285.86549708.216269.79769730.812239.02269761.846209.6517
9773.608204.54319808.395207.23079839.429186.4775 9904.39158.40559994.594149.9038
10056.66 151.30510283.66228.255910388.29250.0221 10602.1253.888910701.45247.5308
10759.39252.756110946.04245.770510997.41235.648511035.83215.378611048.64203.0479
11076.68194.365111112.67191.992911138.28 204.607 11163.9227.388711233.73236.1223
#Mann= 3 , 0 , 0
 8818.88  0.0411       0 8818.88  0.0411       011233.73  0.0411       0
#XS Ineff= 2 , 0
       0                               0
Bank Sta=8818.88,11233.73
Exp/Cntr=0.3,0.1

Type RM Length L Ch R = 1 ,39348.13,608.961000,608.961000,608.961000
XS GIS Cut Line= 3
911991.342313543825478.059878553 912195.09066501823912.108262991
912090.305798541823265.934919766
#Sta/Elev= 30
9441.747199.85489646.519191.0021 9908.71183.31729928.879175.19849949.048158.9299
9969.216139.9097  9979.3134.821310009.55133.641710059.97137.127910090.23146.5995
 10110.4149.062710120.48145.905610211.24144.984510433.09150.1805 10493.6148.5504
10614.61150.068710695.29147.092910745.71147.400610866.72151.058510937.31156.0869
11321.89155.427311483.98160.5841 11524.5165.723511554.89180.386711575.15187.9184
11585.28189.280311605.55196.075711615.68195.939111646.19201.089211675.51209.7431
#Mann= 3 , 0 , 0
9441.747  0.0588       09441.747  0.0588       011675.51  0.0588       0
#XS Ineff= 2 , 0
       0                10581.28       0
Bank Sta=9441.747,11675.51
Exp/Cntr=0.3,0.1

Type RM Length L Ch R = 1 ,38739.17,216.356800,216.356800,216.356800
XS GIS Cut Line= 6
911688.512315322827825.976181538 912263.60286017826617.405014293
912419.470749041826192.993025247912559.389052516825690.238663576
912708.480272827 824652.00962215912867.413306435822755.488066309
#Sta/Elev= 30
7013.291558.85847206.679555.65267395.067538.62357506.729522.30157754.193468.0017
8018.188440.67568149.115405.31458225.232370.40538257.668365.87098322.539328.5228
8352.374324.71028569.188229.99718907.247182.28538959.643 160.7789028.089156.7088
9198.184162.70089239.359183.48269259.946185.01129354.315177.81489474.922181.9897
9586.581151.77169859.194148.41039909.479144.62049939.613133.38929999.775131.5677
10110.19144.925912010.22155.559312080.31179.928812190.44200.110512280.06224.8453
#Mann= 3 , 0 , 0
7013.291    0.04       07013.291    0.04       012280.06    0.04       0
#XS Ineff= 2 , 0
       09867.973        10130.89       0
Bank Sta=7013.291,12280.06
Exp/Cntr=0.3,0.1

Type RM Length L Ch R = 3 ,38596.23,,,
BEGIN DESCRIPTION:
END DESCRIPTION:
Bridge Culvert--1,0,-1,-1, 0
Deck Dist Width WeirC Skew NumUp NumDn MinLoCord MaxHiCord MaxSubmerge Is_Ogee
92.594450,31.167900,2.6,0, 60, 60, , , 0.95, 0, 0,0,,
 9592.20 9612.69 9622.72 9632.74 9642.77 9652.80 9672.85 9682.87 9692.90 9712.95
 9743.03 9773.11 9783.11 9813.14 9883.19 9891.15 9918.45 9918.4510086.7610086.76
10123.9210174.0910254.2910294.3610344.4610374.5210434.6310544.8410585.0210655.48
10685.6810695.7510725.9410746.0710806.4710826.6010866.7610916.8610976.9811127.28
11217.4611297.6111368.0011438.4211458.5411468.6011498.7811649.0411709.5511819.89
11900.1311930.2211970.3512010.4712030.5312050.5912070.6512140.8712180.9912200.33
  146.85  145.25  145.09  145.30  145.84  145.46  145.49  146.49  146.73  144.86
  145.19  145.10  145.40  146.92  151.55  151.94  152.04  152.04  152.70  152.70
  152.76  152.03  151.66  151.18  151.31  150.90  150.90  150.21  150.32  149.66
  149.79  149.51  149.72  149.52  149.89  149.71  149.80  150.15  150.00  151.75
  152.25  153.19  153.56  154.55  154.70  154.40  154.95  156.35  156.59  158.15
  159.80  160.79  162.78  165.62  167.52  169.94  172.65  183.18  189.47  192.24
 -853.15 -854.75 -854.91 -854.70 -854.16 -854.54 -854.51 -853.51 -853.27 -855.14
 -854.81 -854.90 -854.60 -853.08 -848.45 -848.06 -847.96  148.54  149.20 -847.30
 -847.24 -847.97 -848.34 -848.82 -848.69 -849.10 -849.10 -849.79 -849.68 -850.34
 -850.21 -850.49 -850.28 -850.48 -850.11 -850.29 -850.20 -849.85 -850.00 -848.25
 -847.75 -846.81 -846.44 -845.45 -845.30 -845.60 -845.05 -843.65 -843.41 -841.85
 -840.20 -839.21 -837.22 -834.38 -832.48 -830.06 -827.35 -816.82 -810.53 -807.76
 9592.20 9612.69 9622.72 9632.74 9642.77 9652.80 9672.85 9682.87 9692.90 9712.95
 9743.03 9773.11 9783.11 9813.14 9883.19 9891.15 9918.00 9918.0010086.3110086.31
10123.9210174.0910254.2910294.3610344.4610374.5210434.6310544.8410585.0210655.48
10685.6810695.7510725.9410746.0710806.4710826.6010866.7610916.8610976.9811127.28
11217.4611297.6111368.0011438.4211458.5411468.6011498.7811649.0411709.5511819.89
11900.1311930.2211970.3512010.4712030.5312050.5912070.6512140.8712180.9912200.33
  146.85  145.25  145.09  145.30  145.84  145.46  145.49  146.49  146.73  144.86
  145.19  145.10  145.40  146.92  151.55  151.94  152.04  152.04  152.70  152.70
  152.76  152.03  151.66  151.18  151.31  150.90  150.90  150.21  150.32  149.66
  149.79  149.51  149.72  149.52  149.89  149.71  149.80  150.15  150.00  151.75
  152.25  153.19  153.56  154.55  154.70  154.40  154.95  156.35  156.59  158.15
  159.80  160.79  162.78  165.62  167.52  169.94  172.65  183.18  189.47  192.24
 -853.15 -854.75 -854.91 -854.70 -854.16 -854.54 -854.51 -853.51 -853.27 -855.14
 -854.81 -854.90 -854.60 -853.08 -848.45 -848.06 -847.96  148.54  149.20 -847.30
 -847.24 -847.97 -848.34 -848.82 -848.69 -849.10 -849.10 -849.79 -849.68 -850.34
 -850.21 -850.49 -850.28 -850.48 -850.11 -850.29 -850.20 -849.85 -850.00 -848.25
 -847.75 -846.81 -846.44 -845.45 -845.30 -845.60 -845.05 -843.65 -843.41 -841.85
 -840.20 -839.21 -837.22 -834.38 -832.48 -830.06 -827.35 -816.82 -810.53 -807.76
Pier Skew, UpSta & Num, DnSta & Num=  ,9973.89, 2 ,9973.43, 2 , 0 , 0 , 0 ,,
    4.00    4.00
 -847.74  152.26
    4.00    4.00
 -847.74  152.26
Pier Skew, UpSta & Num, DnSta & Num=  ,10031.32, 2 ,10030.87, 2 , 0 , 0 , 0 ,,
    4.00    4.00
 -847.52  152.48
    4.00    4.00
 -847.52  152.48
BR Coef=-1 , 0 , 0 ,, 0 ,,,0.8,0,1,0,
WSPro=,,,, 1 ,,,, 0 ,,,, 0 ,,,,-1 ,-1 ,-1 , 0 , 0 , 0 , 0 , 0
BC Design=,, 0 ,, 0 ,,,,,,

Type RM Length L Ch R = 1 ,38522.81,1521.537400,1521.537400,1521.537400
XS GIS Cut Line= 6
912031.809525277827883.584310595912311.406371905 827298.48756466
912540.120417421826748.440850453912815.329973102825611.390844086
 912936.85775088824430.835288531 913093.10775088822555.835288531
#Sta/Elev= 30
 7019.81494.28797085.176 463.5717219.068416.27197440.951384.38597496.203389.1347
7595.182365.35327801.451290.74277977.148297.4091 8106.74290.92398411.698249.0918
8751.227  171.438802.671172.62628874.692156.01228967.291151.40869049.601176.0934
9080.467178.06279183.354168.9216 9214.22174.54349470.581172.72959510.792169.2068
9581.162146.84579902.853142.14049933.011130.752610013.43129.927210073.75144.2284
10767.09141.903512071.38158.531412141.67168.724412262.16201.233812502.31233.0875
#Mann= 3 , 0 , 0
 7019.81    0.04       0 7019.81    0.04       012502.31    0.04       0
#XS Ineff= 2 , 0
       0  9881.4        10113.82       0
Bank Sta=7019.81,12502.31
Exp/Cntr=0.3,0.1

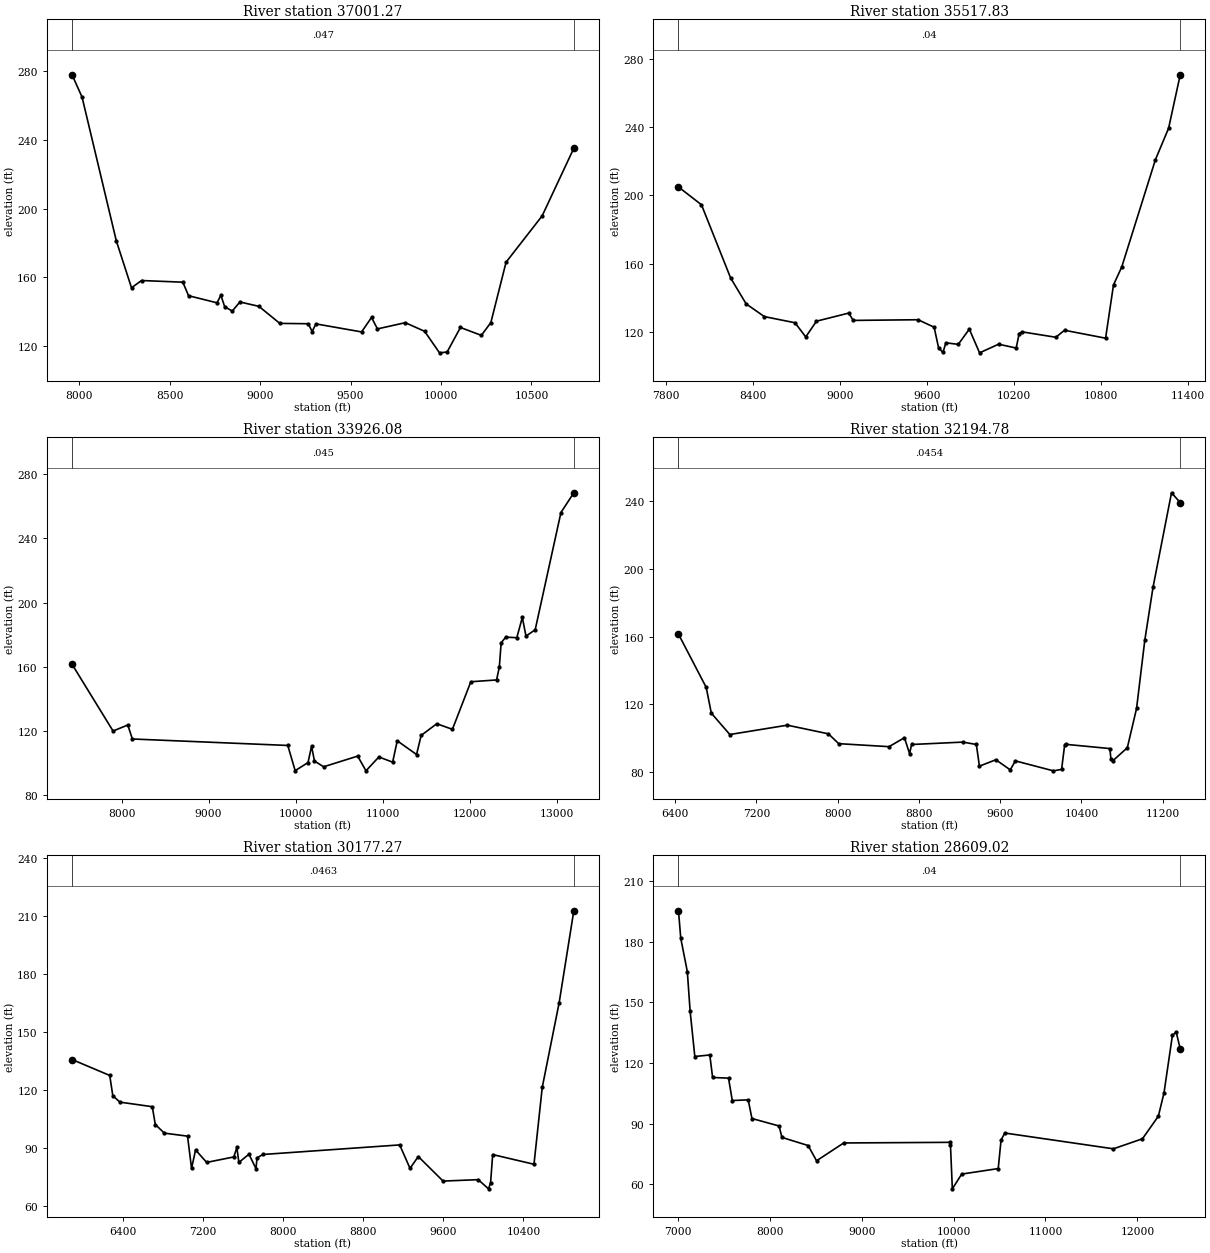
Type RM Length L Ch R = 1 ,37001.27,1483.445100,1483.445100,1483.445100
XS GIS Cut Line= 2
913707.257056435827297.588760753 914557.95150088824658.699871864
#Sta/Elev= 30
 7961.27278.06648016.524265.01618205.646 181.202  8289.7153.76558345.023158.0116
8573.382157.04318604.903149.14768762.504144.99778783.518149.45778804.531142.7468
8846.558140.17478888.585145.49658993.653142.95269109.227132.99439266.829132.7949
9287.842128.20639308.856132.70539561.018128.01999616.127136.45299648.719129.7823
9802.674133.40759909.459 128.3749991.796115.813710033.82116.296410107.37 130.609
10222.94126.012410275.48133.469610359.53168.707510559.16195.778310733.89235.2051
#Mann= 3 , 0 , 0
 7961.27   0.047       0 7961.27   0.047       010733.89   0.047       0
#XS Ineff= 2 , 0
       0                               0
Bank Sta=7961.27,10733.89
Exp/Cntr=0.3,0.1

Type RM Length L Ch R = 1 ,35517.83,1591.751900,1591.751900,1591.751900
XS GIS Cut Line= 3
915174.270945324827775.019316309 915651.70150088826377.449871864
915929.479278657824415.644316309
#Sta/Elev= 30
7886.623204.89888045.154194.46598245.935151.64248352.883136.48088478.418129.0271
8689.766125.41898763.738117.1249 8837.71126.33989059.625131.07289091.328126.7973
9537.661127.19059648.758122.82139679.058110.80199709.357108.06159729.556113.6809
9814.996112.78539891.152121.68699961.851107.814510093.15112.868310214.34110.6151
10234.54119.123410254.74120.091410487.04 116.93210547.64121.027910830.43116.3863
10884.94147.600910941.53158.020211173.82220.854611264.72239.295111344.86270.5604
#Mann= 3 , 0 , 0
7886.623    0.04       07886.623    0.04       011344.86    0.04       0
#XS Ineff= 2 , 0
       09058.685        10298.12       0
Bank Sta=7886.623,11344.86
Exp/Cntr=0.3,0.1

Type RM Length L Ch R = 1 ,33926.08,1731.301800,1731.301800,1731.301800
XS GIS Cut Line= 2
916016.284834213828970.765844087 917878.26400088 823515.03667742
#Sta/Elev= 30
7431.884161.49027902.896 119.9198071.958123.6602 8124.79114.95189910.503110.9212
9995.03495.1929910142.96100.269610183.36110.471910216.93101.168210322.5997.64181
10713.55 104.28810808.6495.1015410956.57103.755211115.07100.5123 11167.9113.8211
11389.79105.279211442.62117.185211622.25124.457311801.88120.970512013.21150.6199
12309.07151.754712340.76159.7223 12361.9174.916412414.73178.429212541.52178.0784
12604.92190.686212647.19 179.08412752.85183.021113048.71256.0974 13196.6268.3993
#Mann= 3 , 0 , 0
7431.884   0.045       07431.884   0.045       0 13196.6   0.045       0
#XS Ineff= 2 , 0
       09789.862        11183.65       0
Bank Sta=7431.884,13196.6
Exp/Cntr=0.3,0.1

Type RM Length L Ch R = 1 ,32194.78,2017.505500,2017.505500,2017.505500
XS GIS Cut Line= 2
917930.848135495829934.724845155918657.635996072825050.034340347
#Sta/Elev= 30
6433.467161.40166706.161129.92326756.711114.65276938.693102.01557504.858107.5449
7909.261102.42578010.36296.607298505.756 94.82718657.407100.13588707.95890.71844
8728.17896.115829233.68297.528149365.113 96.12159395.44483.294729557.20587.08704
9698.74681.109189749.297 86.411110123.3780.5284110204.2581.3768710234.5895.93626
10244.6996.2121910679.4293.7093710689.5387.6667510709.7586.54745 10851.394.20764
10942.29117.499411023.17157.799211104.05189.074611286.03245.034411371.93239.2468
#Mann= 3 , 0 , 0
6433.467  0.0454       06433.467  0.0454       011371.93  0.0454       0
#XS Ineff= 2 , 0
       09260.001        10431.74       0
Bank Sta=6433.467,11371.93
Exp/Cntr=0.3,0.1

Type RM Length L Ch R = 1 ,30177.27,1568.252300,1568.252300,1568.252300
XS GIS Cut Line= 4
919342.168748476 829816.41054227919232.305467226829123.426768232
 919460.48305136826841.650926886919950.642306168 824889.46492929
#Sta/Elev= 30
5894.706135.77316270.755127.5555 6301.13117.12616372.004113.78796695.262111.4326
6725.412102.23196815.86197.782937047.008 96.22847087.20879.603097127.40789.10659
7237.95682.676147509.30285.496257539.452 90.40677559.55282.66251 7660.0586.90013
  7730.479.436657740.44985.053627800.74986.770479164.42991.705789267.53379.60475
9350.01685.708419597.46573.035019948.01973.7695710051.12  69.03110071.74 72.1965
10092.3686.7257110504.7881.7155410587.26121.406410755.92165.076410902.28  212.56
#Mann= 3 , 0 , 0
5894.706  0.0463       05894.706  0.0463       010902.28  0.0463       0
#XS Ineff= 2 , 0
       09089.111                       0
Bank Sta=5894.706,10902.28
Exp/Cntr=0.3,0.1

Type RM Length L Ch R = 1 ,28609.02,2782.478500,2782.478500,2782.478500
XS GIS Cut Line= 2
919823.876981649829909.371780251 920888.70570761824551.424063905
#Sta/Elev= 30
7004.214195.36357029.062181.75037100.431 165.2847131.018145.68747181.996123.2763
7345.125124.03757375.712112.89667549.037112.58667589.819101.49027763.144101.8429
7803.92692.611068099.59788.898858130.18483.26486 8415.6679.23693 8507.4271.69283
8803.09280.509779955.19280.818939965.38779.442549985.77857.8175110087.7365.11282
10485.3667.8423810515.95 81.898810556.7385.4315111739.4277.6208912055.4882.57515
 12228.893.7487112289.98105.227512381.74133.712112422.52135.431212466.95127.0725
#Mann= 3 , 0 , 0
7004.214    0.04       07004.214    0.04       012466.95    0.04       0
#XS Ineff= 2 , 0
       09853.409                       0
Bank Sta=7004.214,12466.95
Exp/Cntr=0.3,0.1

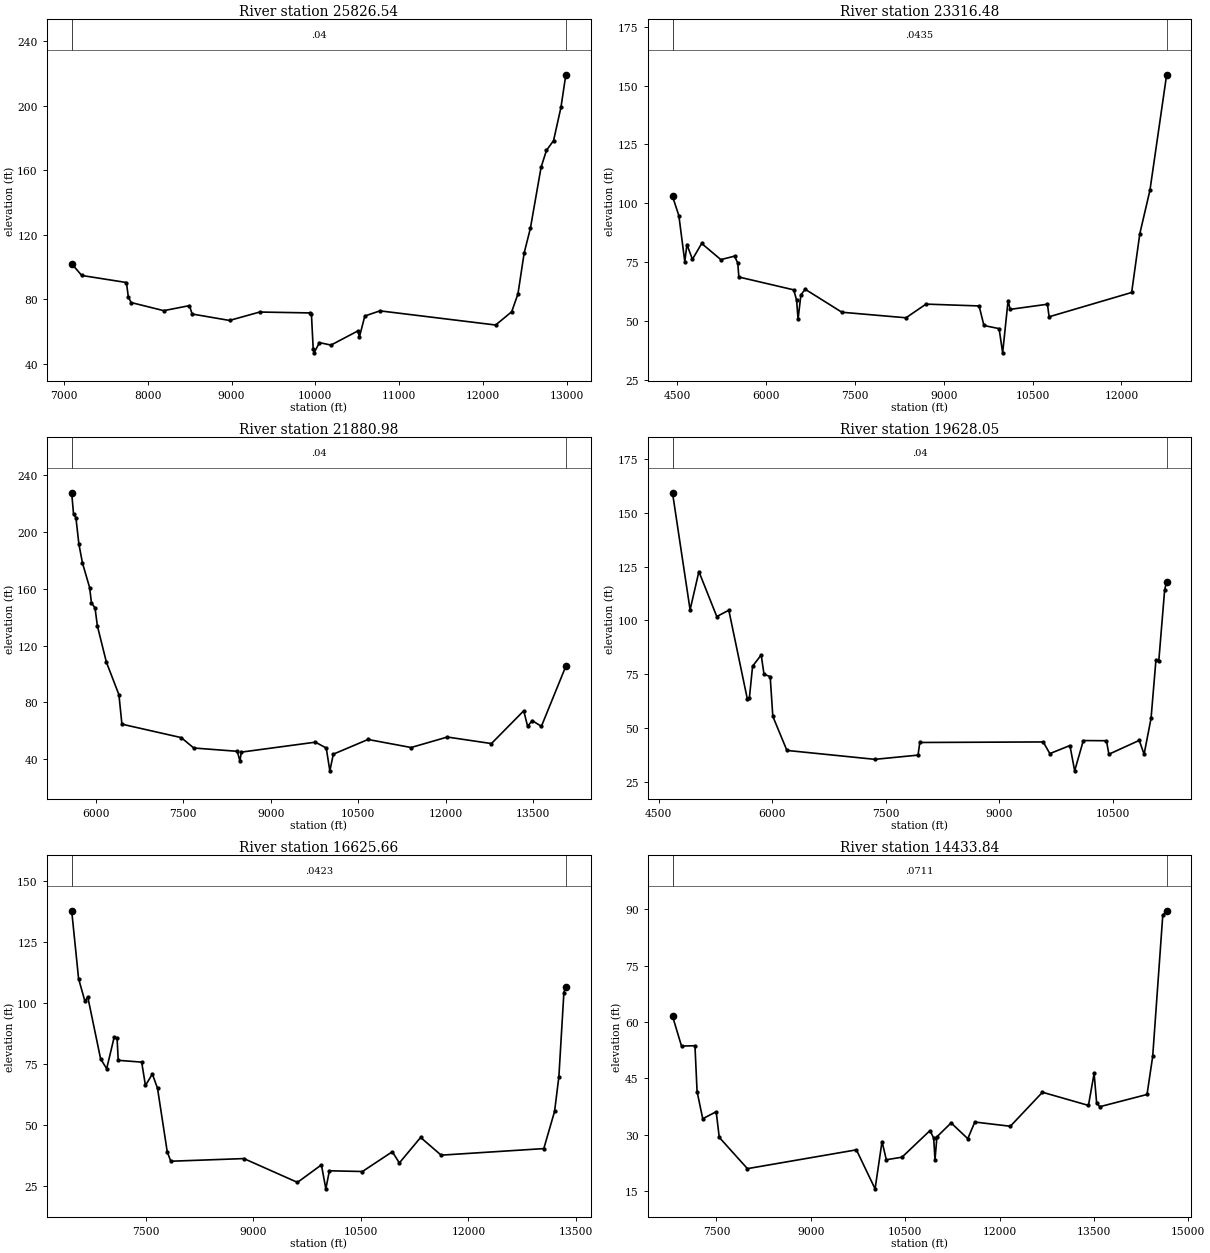
Type RM Length L Ch R = 1 ,25826.54,2510.062100,2510.062100,2510.062100
XS GIS Cut Line= 3
920582.257056435830591.859594087921155.173723102829419.984594087
922704.652889768 825097.06792742
#Sta/Elev= 30
7092.724102.02967212.80994.756257745.96290.398757768.22581.593147801.61877.98827
8191.20672.95254 8498.0576.079418529.91970.870328976.08466.900039337.26572.10509
9932.15171.560039953.39770.941929974.643 49.38729985.26646.82106   1004953.14989
 10187.151.6311310505.7960.3344910527.0456.8119610590.7869.6506610771.3772.83151
12152.3564.0594512343.5772.3045712417.9383.2850312492.29108.723912566.65124.0379
12694.03161.806112757.86  172.2212842.84178.319612931.12198.897712989.37219.1058
#Mann= 3 , 0 , 0
7092.724    0.04       07092.724    0.04       012989.37    0.04       0
#XS Ineff= 2 , 0
       09825.123                       0
Bank Sta=7092.724,12989.37
Exp/Cntr=0.3,0.1

Type RM Length L Ch R = 1 ,23316.48,1435.494700,1435.494700,1435.494700
XS GIS Cut Line= 4
920998.923723102832584.047094087922287.986223102830669.984594087
924202.048723102827466.859594087925321.840389768 825448.63042742
#Sta/Elev= 30
4415.821103.01074523.17994.789324623.61975.240414659.42382.53508 4752.25 76.2648
4908.98382.988945232.28376.117225463.57677.597975518.714 74.63935536.61568.74067
6464.25563.286816512.48158.844316536.59350.768636584.81961.181886657.15763.54669
7276.81353.788458360.20551.430488698.03757.236849595.03856.458619676.58448.15782
 9932.8746.828839992.802  36.55110084.3158.7113510119.2655.0044610749.5757.18798
10777.26 51.856912171.7762.16974 12309.787.1134912481.24105.631912762.99154.5937
#Mann= 3 , 0 , 0
4415.821  0.0435       04415.821  0.0435       012762.99  0.0435       0
#XS Ineff= 2 , 0
       09021.357        10269.33       0
Bank Sta=4415.821,12762.99
Exp/Cntr=0.3,0.1

Type RM Length L Ch R = 1 ,21880.98,2252.936200,2252.936200,2252.936200
XS GIS Cut Line= 4
922912.986223102832935.609594087923225.486223102831516.338760753
925165.590389768828013.734594087926558.819556435825344.463760753
#Sta/Elev= 30
5590.206227.33385621.549212.50275662.507209.92345713.704191.30395775.142177.9715
5898.016160.67065928.735150.09345990.172146.3543 6031.13133.66356184.723108.3667
6399.75385.439146450.95164.758937467.97255.309327682.25448.011728428.22445.69264
 8473.9538.758178496.81445.120219766.714 52.10849952.45848.0225610014.3731.96893
10074.3743.6876710668.8154.0071511407.0448.3573612027.4555.7142212783.2351.12783
13337.0674.1434913403.6463.26059 13482.6 67.267713639.6263.22533 14058.5105.4401
#Mann= 3 , 0 , 0
5590.206    0.04       05590.206    0.04       0 14058.5    0.04       0
#XS Ineff= 2 , 0
       09766.907        10681.91       0
Bank Sta=5590.206,14058.5
Exp/Cntr=0.3,0.1

Type RM Length L Ch R = 1 ,19628.05,3002.388800,3002.388800,3002.388800
XS GIS Cut Line= 6
923485.902889768 833104.88042742 925289.54975743830100.291920308
925899.650813552829619.472373322926389.385636731829365.945982145
926537.499052845829258.994579702927492.471223273828084.638928364
#Sta/Elev= 30
4681.722159.26684914.254104.90495030.589122.67065267.044101.7848 5426.13104.7051
5670.43563.553875697.57563.828345740.23678.705225854.13283.937865891.47274.92292
5972.90773.901846007.80855.415876193.94439.592917357.299 35.45357927.34337.41959
 7950.6143.28357 9581.7943.536079669.65538.113039935.035  41.8699997.60630.11232
10112.3444.1800110417.8844.0973110449.9837.8250910851.26 44.254410915.3537.83139
11007.2654.4838911071.5681.3762311110.1481.3550211187.31 114.25211213.49117.9183
#Mann= 3 , 0 , 0
4681.722    0.04       04681.722    0.04       011213.49    0.04       0
#XS Ineff= 2 , 0
       09456.878        10405.11       0
Bank Sta=4681.722,11213.49
Exp/Cntr=0.3,0.1

Type RM Length L Ch R = 1 ,16625.66,2191.815600,2191.815600,2191.815600
XS GIS Cut Line= 5
923802.371467754833104.991393804924568.000244513832213.454230845
927600.020623069830016.437207105927641.687289736829919.214984883
 927711.13173418828058.103873772
#Sta/Elev= 30
 6469.68137.85026565.809110.02956654.208 100.7446693.752102.54686872.79177.17072
 6957.38 73.12187062.83186.148947102.37685.594117118.37676.553077445.09275.80895
7497.81866.255277594.19870.914777665.84465.124177801.686 39.03567851.08335.18426
8869.29836.273719617.03426.519689950.46533.6944310012.2123.8701310061.6131.26801
10522.4530.9746710938.4139.06993 11037.234.4866411333.5944.9362611619.2637.67691
13050.2540.3657713200.3655.59602 13260.469.8300213330.45104.342913357.36106.7838
#Mann= 3 , 0 , 0
 6469.68  0.0423       0 6469.68  0.0423       013357.36  0.0423       0
#XS Ineff= 2 , 0
       09473.353        11370.51       0
Bank Sta=6469.68,13357.36
Exp/Cntr=0.3,0.1

Type RM Length L Ch R = 1 ,14433.84,287.419400,287.419400,287.419400
XS GIS Cut Line= 6
925583.937870738835372.210238451  926053.2199721834463.600212409
927496.319556435831752.449871864927600.852434039831288.457484044
927697.791517155830706.822985351927840.485847501828013.467500069
#Sta/Elev= 30
6800.66461.565666943.83953.606947157.68453.68981 7191.4541.51118 7281.4934.30645
7495.33536.167167543.89429.357847991.74421.049679724.43426.04642 10021.515.68693
10132.0228.2540910199.9623.4152210449.2924.0908810894.6131.16281 10953.529.14214
   1097423.3719211004.7529.5035711230.2733.1976411495.3929.0006411606.9133.42629
12172.0132.3053712682.7241.3384313413.7537.8377413503.87 46.344913543.9338.48262
   1359437.4988414345.0540.7481214435.1850.84861 14595.488.3339814657.0289.53339
#Mann= 3 , 0 , 0
6800.664  0.0711       06800.664  0.0711       014657.02  0.0711       0
#XS Ineff= 2 , 0
       09768.451        10219.64       0
Bank Sta=6800.664,14657.02
Exp/Cntr=0.3,0.1

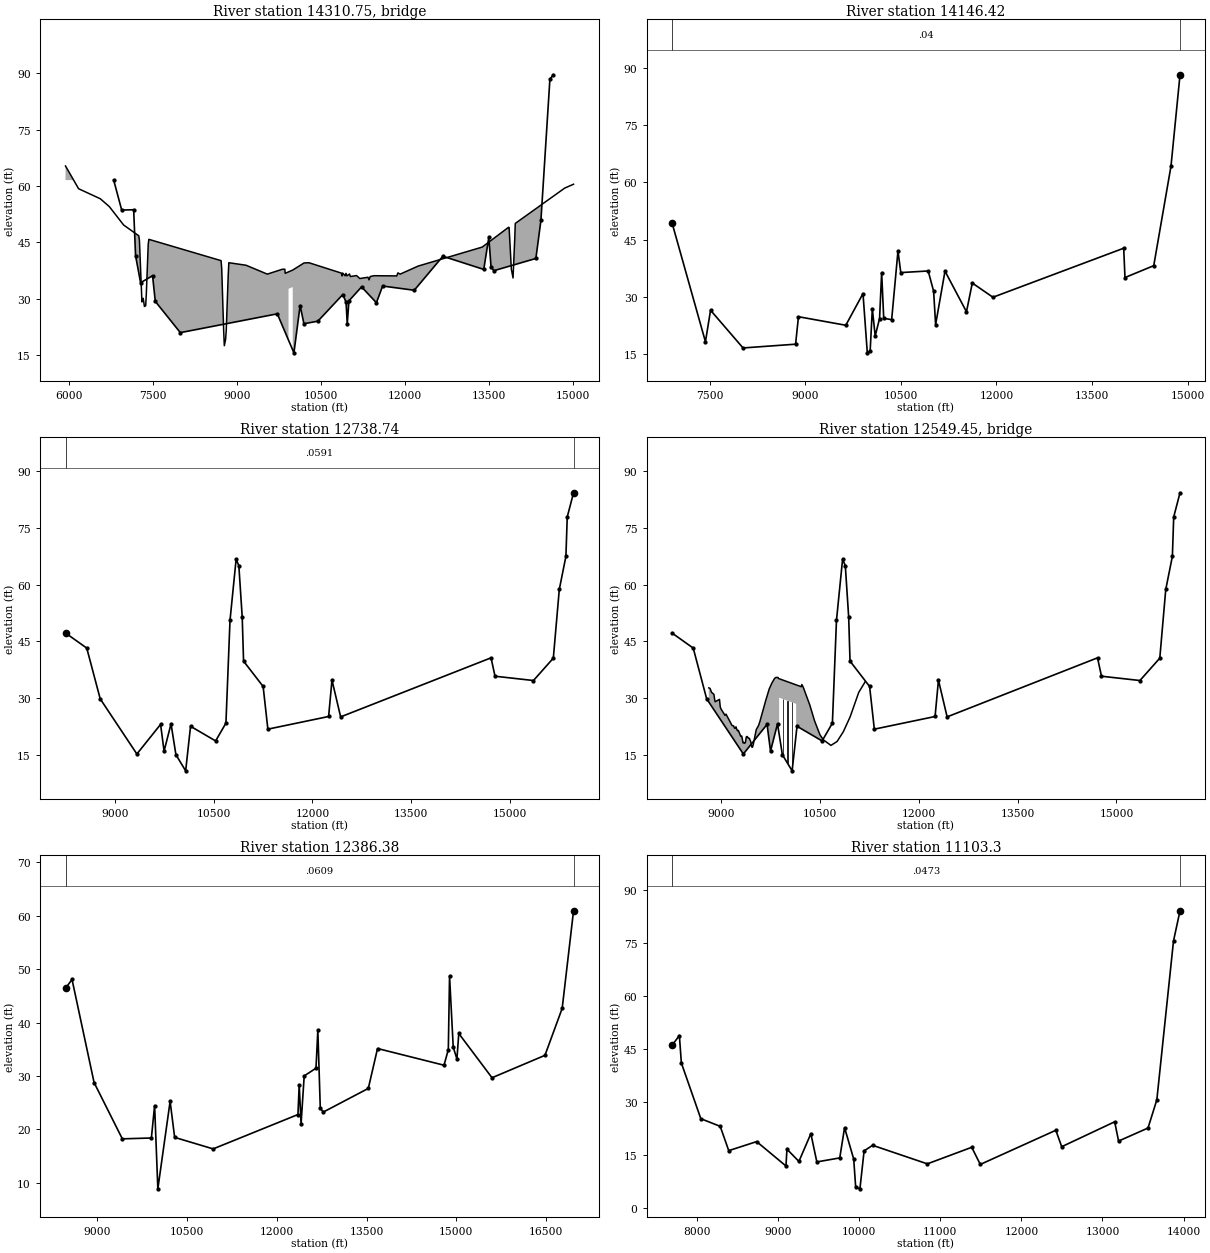
Type RM Length L Ch R = 3 ,14310.75,,,
BEGIN DESCRIPTION:
END DESCRIPTION:
Bridge Culvert--1,0,-1,-1, 0
Deck Dist Width WeirC Skew NumUp NumDn MinLoCord MaxHiCord MaxSubmerge Is_Ogee
97.449950,92.519500,2.6,0, 60, 60, , , 0.95, 0, 0,0,,
 5939.74 6173.56 6561.09 6722.46 6978.48 7249.26 7260.49 7305.40 7327.86 7350.31
 7372.77 7384.00 7417.68 7428.91 8719.86 8731.39 8766.00 8777.53 8800.60 8812.14
 8846.74 8858.28 9166.52 9545.67 9813.31 9858.54 9865.16 9924.87 9924.8710000.00
10000.0010202.5810289.0110870.4110881.5510892.6810935.3410951.2610966.9711014.51
11030.2111141.0011198.8711343.9711364.1911384.4011451.0711859.3011879.4111919.64
12241.4513385.3513856.6813866.7113906.8213936.9113966.9913977.0214859.5115018.20
   65.31   59.27   56.61   54.53   49.63   46.77   45.65   29.20   30.17   27.99
   28.21   31.41   44.48   45.83   40.17   37.98   21.65   17.58   19.25   21.73
   36.11   39.62   38.95   36.59   37.88   37.90   36.81   37.19   37.19   37.67
   37.67   39.56   39.62   36.86   36.11   36.87   36.16   36.79   36.14   36.62
   35.95   36.21   35.42   35.76   35.06   35.95   36.17   36.12   36.92   36.59
   38.73   43.77   49.03   48.96   37.91   35.57   45.78   50.06   59.43   60.47
 -934.69 -940.73 -943.39 -945.47 -950.37 -953.23 -954.35 -970.80 -969.83 -972.01
 -971.79 -968.59 -955.52 -954.17 -959.83 -962.02 -978.35 -982.42 -980.75 -978.27
 -963.89 -960.38 -961.05 -963.41 -962.12 -962.10 -963.19 -962.81   32.69   33.17
 -962.33 -960.44 -960.38 -963.14 -963.89 -963.13 -963.84 -963.21 -963.86 -963.38
 -964.05 -963.79 -964.58 -964.24 -964.94 -964.05 -963.83 -963.88 -963.08 -963.41
 -961.27 -956.23 -950.97 -951.04 -962.09 -964.43 -954.22 -949.94 -940.57 -939.53
 5939.74 6173.56 6561.09 6722.46 6978.48 7249.26 7260.49 7305.40 7327.86 7350.31
 7372.77 7384.00 7417.68 7428.91 8719.86 8731.39 8766.00 8777.53 8800.60 8812.14
 8846.74 8858.28 9166.52 9545.67 9813.31 9858.54 9865.1610000.0010000.0010075.13
10075.1310202.5810289.0110870.4110881.5510892.6810935.3410951.2610966.9711014.51
11030.2111141.0011198.8711343.9711364.1911384.4011451.0711859.3011879.4111919.64
12241.4513385.3513856.6813866.7113906.8213936.9113966.9913977.0214859.5115018.20
   65.31   59.27   56.61   54.53   49.63   46.77   45.65   29.20   30.17   27.99
   28.21   31.41   44.48   45.83   40.17   37.98   21.65   17.58   19.25   21.73
   36.11   39.62   38.95   36.59   37.88   37.90   36.81   37.67   37.67   38.16
   38.16   39.56   39.62   36.86   36.11   36.87   36.16   36.79   36.14   36.62
   35.95   36.21   35.42   35.76   35.06   35.95   36.17   36.12   36.92   36.59
   38.73   43.77   49.03   48.96   37.91   35.57   45.78   50.06   59.43   60.47
 -934.69 -940.73 -943.39 -945.47 -950.37 -953.23 -954.35 -970.80 -969.83 -972.01
 -971.79 -968.59 -955.52 -954.17 -959.83 -962.02 -978.35 -982.42 -980.75 -978.27
 -963.89 -960.38 -961.05 -963.41 -962.12 -962.10 -963.19 -962.33   33.17   33.66
 -961.84 -960.44 -960.38 -963.14 -963.89 -963.13 -963.84 -963.21 -963.86 -963.38
 -964.05 -963.79 -964.58 -964.24 -964.94 -964.05 -963.83 -963.88 -963.08 -963.41
 -961.27 -956.23 -950.97 -951.04 -962.09 -964.43 -954.22 -949.94 -940.57 -939.53
BR Coef=-1 , 0 , 0 ,, 0 ,,,0.8,0,1,0,
WSPro=,,,, 1 ,,,, 0 ,,,, 0 ,,,,-1 ,-1 ,-1 , 0 , 0 , 0 , 0 , 0
BC Design=,, 0 ,, 0 ,,,,,,

Type RM Length L Ch R = 1 ,14146.42,1407.685300,1407.685300,1407.685300
XS GIS Cut Line= 6
925803.601833078835442.103317377926652.303505754833964.363934364
927441.096825065832436.700923547927800.546945257831568.029799749
927970.287279793830519.633615854928179.966516571827983.513323386
#Sta/Elev= 30
 6908.8149.463357433.95618.316267514.31626.549018023.86616.688198848.55117.67427
8893.56924.859159636.35722.624189906.46130.914889973.98715.41161   1001915.96834
10052.77 26.895810097.7919.8338610166.3524.3729110199.07 36.384710231.7424.43666
10356.1424.0892310455.3742.0699510499.4736.3989710929.4536.8211311014.4131.53767
11045.9422.8036811193.0436.7737611530.2426.1495411621.4133.6677811945.5829.94712
13997.3142.7746314017.37 35.101914468.8538.20831 14739.464.2321414881.0488.12928
#Mann= 3 , 0 , 0
 6908.81    0.04       0 6908.81    0.04       014881.04    0.04       0
#XS Ineff= 2 , 0
       09805.572        10196.11       0
Bank Sta=6908.81,14881.04
Exp/Cntr=0.3,0.1

Type RM Length L Ch R = 1 ,12738.74,352.352000,352.352000,352.352000
XS GIS Cut Line= 6
926765.416778658835452.970705198927355.694556435834498.109594087
927755.000111991833334.915149642927824.444556435833057.137371865
928136.944556435831650.887371865 928518.88900088828039.776260753
#Sta/Elev= 30
8253.44447.217578575.95543.23995  8780.129.851429336.66815.303799696.49723.11311
9749.36116.062069855.08923.261579929.09915.1166510077.1210.8645510151.1322.61881
10531.7518.7497110688.22 23.450210750.0750.5554410842.84 66.658210884.0764.99794
10935.3451.4150510955.83 39.7961 11252.933.1123811324.6121.8573912246.5625.19599
12297.7834.7844912429.1525.0932514711.8140.6686614772.1535.8189415355.3834.68379
15657.0640.5782315747.5658.6995215848.1267.4318815868.2377.8188815963.9884.19839
#Mann= 3 , 0 , 0
8253.444  0.0591       08253.444  0.0591       015963.98  0.0591       0
#XS Ineff= 2 , 0
       0                10833.93       0
Bank Sta=8253.444,15963.98
Exp/Cntr=0.3,0.1

Type RM Length L Ch R = 3 ,12549.45,,,
BEGIN DESCRIPTION:
END DESCRIPTION:
Bridge Culvert--1,0,-1,-1, 0
Deck Dist Width WeirC Skew NumUp NumDn MinLoCord MaxHiCord MaxSubmerge Is_Ogee
141.176000,70.000000,2.6,0, 60, 60, , , 0.95, 0, 0,0,,
 8812.52 8831.48 8853.34 8890.03 8903.04 8908.38 8974.60 8986.53 8998.46 9058.09
 9073.52 9165.27 9189.29 9201.21 9213.14 9225.07 9236.99 9248.92 9260.85 9296.63
 9312.06 9332.41 9344.33 9356.26 9368.19 9380.11 9392.04 9415.90 9427.82 9451.68
 9463.60 9475.53 9487.46 9532.25 9566.06 9586.46 9678.24 9729.35 9770.27 9811.20
 9831.66 9862.58 9868.35 9879.72 9879.7210137.7210137.7210216.1610224.1110245.11
10346.6110417.6610499.5910550.9910665.7110759.5910855.1610957.6011088.1711183.22
   32.75   32.61   31.59   31.03   29.49   29.09   29.71   27.70   27.16   25.50
   25.82   22.82   22.71   22.15   22.07   22.47   21.81   21.43   21.53   19.97
   20.06   18.23   18.34   18.14   18.33   19.73   19.94   19.45   19.44   18.42
   17.16   17.09   17.80   21.73   22.77   23.80   29.54   32.46   34.04   35.25
   35.50   35.49   35.23   35.16   35.16   33.54   33.54   33.05   33.63   32.95
   28.16   24.04   20.36   19.05   17.57   18.61   21.21   25.11   31.56   34.29
 -967.25 -967.39 -968.41 -968.97 -970.51 -970.91 -970.29 -972.30 -972.84 -974.50
 -974.18 -977.18 -977.29 -977.85 -977.93 -977.53 -978.19 -978.57 -978.47 -980.03
 -979.94 -981.77 -981.66 -981.86 -981.67 -980.27 -980.06 -980.55 -980.56 -981.58
 -982.84 -982.91 -982.20 -978.27 -977.23 -976.20 -970.46 -967.54 -965.96 -964.75
 -964.50 -964.51 -964.77 -964.84   30.16   28.54 -966.46 -966.95 -966.37 -967.05
 -971.84 -975.96 -979.64 -980.95 -982.43 -981.39 -978.79 -974.89 -968.44 -965.71
 8812.52 8831.48 8853.34 8890.03 8903.04 8908.38 8974.60 8986.53 8998.46 9058.09
 9073.52 9165.27 9189.29 9201.21 9213.14 9225.07 9236.99 9248.92 9260.85 9296.63
 9312.06 9332.41 9344.33 9356.26 9368.19 9380.11 9392.04 9415.90 9427.82 9451.68
 9463.60 9475.53 9487.46 9532.25 9566.06 9586.46 9698.66 9729.35 9749.81 9800.97
 9831.66 9862.58 9868.35 9956.04 9956.0410214.0410214.0410224.1110245.1110346.61
10417.6610499.5910550.9910665.7110719.0110759.5910855.1610957.6011088.1711183.22
   32.75   32.61   31.59   31.03   29.49   29.09   29.71   27.70   27.16   25.50
   25.82   22.82   22.71   22.15   22.07   22.47   21.81   21.43   21.53   19.97
   20.06   18.23   18.34   18.14   18.33   19.73   19.94   19.45   19.44   18.42
   17.16   17.09   17.80   21.73   22.77   23.80   30.74   32.46   33.30   35.05
   35.50   35.49   35.23   34.68   34.68   33.06   33.06   33.63   32.95   28.16
   24.04   20.36   19.05   17.57   18.03   18.61   21.21   25.11   31.56   34.29
 -967.25 -967.39 -968.41 -968.97 -970.51 -970.91 -970.29 -972.30 -972.84 -974.50
 -974.18 -977.18 -977.29 -977.85 -977.93 -977.53 -978.19 -978.57 -978.47 -980.03
 -979.94 -981.77 -981.66 -981.86 -981.67 -980.27 -980.06 -980.55 -980.56 -981.58
 -982.84 -982.91 -982.20 -978.27 -977.23 -976.20 -969.26 -967.54 -966.70 -964.95
 -964.50 -964.51 -964.77 -965.32   29.68   28.06 -966.94 -966.37 -967.05 -971.84
 -975.96 -979.64 -980.95 -982.43 -981.97 -981.39 -978.79 -974.89 -968.44 -965.71
Pier Skew, UpSta & Num, DnSta & Num=  ,9943.22, 2 ,10019.54, 2 , 0 , 0 , 0 ,,
    4.00    4.00
 -965.24   34.76
    4.00    4.00
 -965.72   34.28
Pier Skew, UpSta & Num, DnSta & Num=  ,10008.72, 2 ,10085.04, 2 , 0 , 0 , 0 ,,
    4.00    4.00
 -965.65   34.35
    4.00    4.00
 -966.13   33.87
Pier Skew, UpSta & Num, DnSta & Num=  ,10074.22, 2 ,10150.54, 2 , 0 , 0 , 0 ,,
    4.00    4.00
 -966.06   33.94
    4.00    4.00
 -966.54   33.46
BR Coef=-1 , 0 , 0 ,, 0 ,,,0.8,0,1,0,
WSPro=,,,, 1 ,,,, 0 ,,,, 0 ,,,,-1 ,-1 ,-1 , 0 , 0 , 0 , 0 , 0
BC Design=,, 0 ,, 0 ,,,,,,

Type RM Length L Ch R = 1 ,12386.38,1283.083400,1283.083400,1283.083400
XS GIS Cut Line= 5
927060.555667546835539.776260753927616.111223102834567.554038531
927963.333445324833716.859594087928553.611223102831720.331816309
929584.861223102827470.331816309
#Sta/Elev= 30
 8467.5146.416548576.669 48.07148945.229  28.7559417.44718.206019903.25318.36431
9957.25824.4441610011.268.83745410216.4825.2313310292.0918.4806110935.5816.32109
12353.7722.7595312374.6328.3386612405.9121.0121912458.0529.9947412655.28 31.4418
12686.1538.5134912727.3123.9103412778.7623.2308913529.95 27.6544 13684.335.13134
14795.64  32.00214867.6734.9258714888.2548.7089614949.9935.3620315011.7333.17922
 15042.637.9474115598.2729.6530516483.2333.8527416771.35 42.651216961.38 60.9409
#Mann= 3 , 0 , 0
 8467.51  0.0609       0 8467.51  0.0609       016961.38  0.0609       0
#XS Ineff= 2 , 0
       0                11062.37       0
Bank Sta=8467.51,16961.38
Exp/Cntr=0.3,0.1

Type RM Length L Ch R = 1 , 11103.3,2425.221500,2425.221500,2425.221500
XS GIS Cut Line= 3
927608.298723102836069.290149642929403.871639769833553.665149642
931190.329973102830928.665149642
#Sta/Elev= 30
7690.19846.113267781.47148.905377806.04341.129128045.99125.357158285.19823.18661
8390.24916.306748734.50818.865749096.07611.960389108.36216.723639255.79513.24852
9403.22721.106819476.94313.109349759.52214.248939818.92122.812399931.52613.92778
9956.0985.93015810008.265.487343 10059.916.2417310164.9617.8152810839.7712.56139
11387.2217.2543711492.9612.4000212424.3622.0776912496.9317.4178613150.1224.47668
13198.5119.0201613561.3922.7135913670.2530.6993613875.8975.7093913956.1384.24805
#Mann= 3 , 0 , 0
7690.198  0.0473       07690.198  0.0473       013956.13  0.0473       0
#XS Ineff= 2 , 0
       0                11042.49       0
Bank Sta=7690.198,13956.13
Exp/Cntr=0.3,0.1

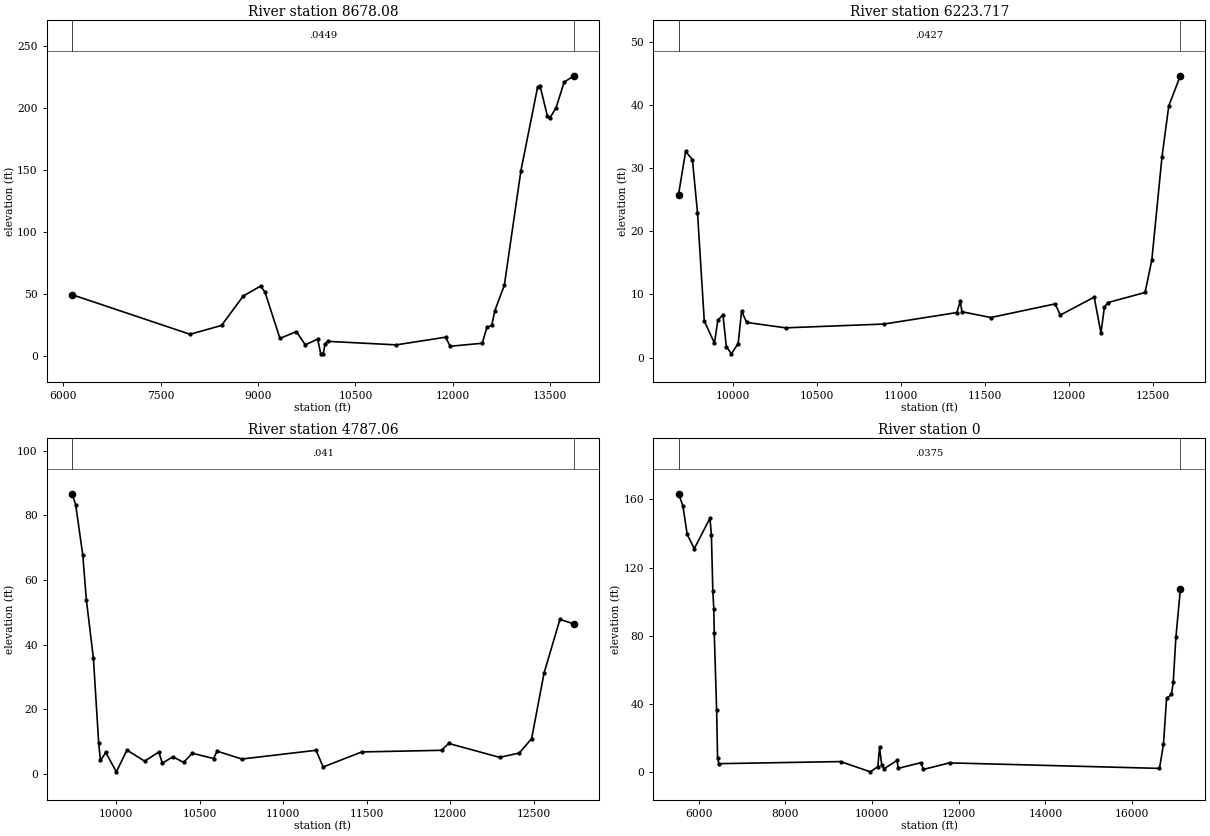
Type RM Length L Ch R = 1 , 8678.08,2454.362600,2454.362600,2454.362600
XS GIS Cut Line= 6
 928503.85287215838305.173513414929822.502085332835516.281672042
929966.068402999835310.051017713930325.547207342834930.109044546
931150.560026645833518.553318445932421.135242508831683.865261257
#Sta/Elev= 30
6135.03449.488087951.289 17.61018437.31324.708268773.742  48.478 9039.4856.41019
9107.17551.546949337.07914.250339590.29919.788189728.0059.085292 9917.4713.69188
9966.6511.85161710003.381.84790410033.229.89675510074.46 11.918311128.849.061293
11888.5715.2611511960.367.94720812453.8610.3815112525.28 23.214712599.2324.68792
12647.8136.6114812793.9157.0224113049.72149.406313308.15217.034113345.04217.4038
13455.78 193.74113492.86191.469113591.74200.131413715.35220.612513865.07225.7734
#Mann= 3 , 0 , 0
6135.034  0.0449       06135.034  0.0449       013865.07  0.0449       0
#XS Ineff= 2 , 0
       08903.382        11939.56       0
Bank Sta=6135.034,13865.07
Exp/Cntr=0.3,0.1

Type RM Length L Ch R = 1 ,6223.717,1436.657400,1436.657400,1436.657400
XS GIS Cut Line= 2
931434.345397781836386.828419207931859.009234921833426.858091682
#Sta/Elev= 30
9675.16125.817169717.41832.626129757.82831.350539788.13522.957329828.5445.793217
9889.1592.2800479909.3645.8827729939.6716.7841789959.8761.7497469990.183 0.58936
10030.592.223354 10050.87.362677 10081.1 5.5596210313.464.706679 10899.45.305879
 11333.87.12449211354.018.93414911364.117.25142311535.856.34162811919.748.495937
11950.05 6.7247512152.099.566185 12192.53.86658412212.717.95082912232.918.700856
12455.1710.3027712495.58 15.435712556.1931.79059 12596.639.8477412665.4444.61419
#Mann= 3 , 0 , 0
9675.161  0.0427       09675.161  0.0427       012665.44  0.0427       0
#XS Ineff= 2 , 0
       0                               0
Bank Sta=9675.161,12665.44
Exp/Cntr=0.3,0.1

Type RM Length L Ch R = 1 , 4787.06,4787.060000,4787.060000,4787.060000
XS GIS Cut Line= 2
932892.146629752836215.695231106931909.715364728833376.151961875
#Sta/Elev= 30
9736.07186.638229757.92983.198549800.29667.63659 9821.4653.883749863.78635.79684
9895.5319.4400319906.1134.1408899937.8576.61247210001.35  0.611910064.847.351041
10170.653.91305610255.316.74080410276.473.29347710339.965.26264210403.453.543667
10456.366.36703210583.34 4.72649 10604.57.01556910752.644.57742111197.077.278903
11239.392.10348311470.656.77148311948.367.27480311990.699.40630612296.425.089917
12413.956.43487512488.02 10.8915 12562.131.1405312657.3347.7790812740.7646.36926
#Mann= 3 , 0 , 0
9736.071   0.041       09736.071   0.041       012740.76   0.041       0
#XS Ineff= 2 , 0
       0                               0
Bank Sta=9736.071,12740.76
Exp/Cntr=0.3,0.1

Type RM Length L Ch R = 1 ,       0,0.000000,0.000000,0.000000
XS GIS Cut Line= 6
933093.798187384  839268.6285545935743.036969435837667.566855782
935429.587319899835713.275585249935581.778956615833451.821663474
935125.801089408830536.228975114935362.928796358829454.926631423
#Sta/Elev= 30
5533.818163.35465633.889156.34775732.641139.57625897.228131.1173 6259.32149.0163
6292.238138.97576325.155106.4731  6347.195.831586358.07381.504186412.93536.26163
 6434.88 8.03701 6465.894.7974419271.7336.0283449961.333       0 10132.13.095216
10172.2714.3623810222.473.79976510272.681.74430210573.596.69751110603.632.054902
11123.885.37030711183.961.41341411787.03 5.2709816630.022.02291616722.1616.08758
16793.8243.1208716906.4345.4652216947.38 52.502517008.8178.9400817111.26107.1221
#Mann= 3 , 0 , 0
5533.818  0.0375       05533.818  0.0375       017111.26  0.0375       0
#XS Ineff= 2 , 0
       0                               0
Bank Sta=5533.818,17111.26
Exp/Cntr=0.3,0.1